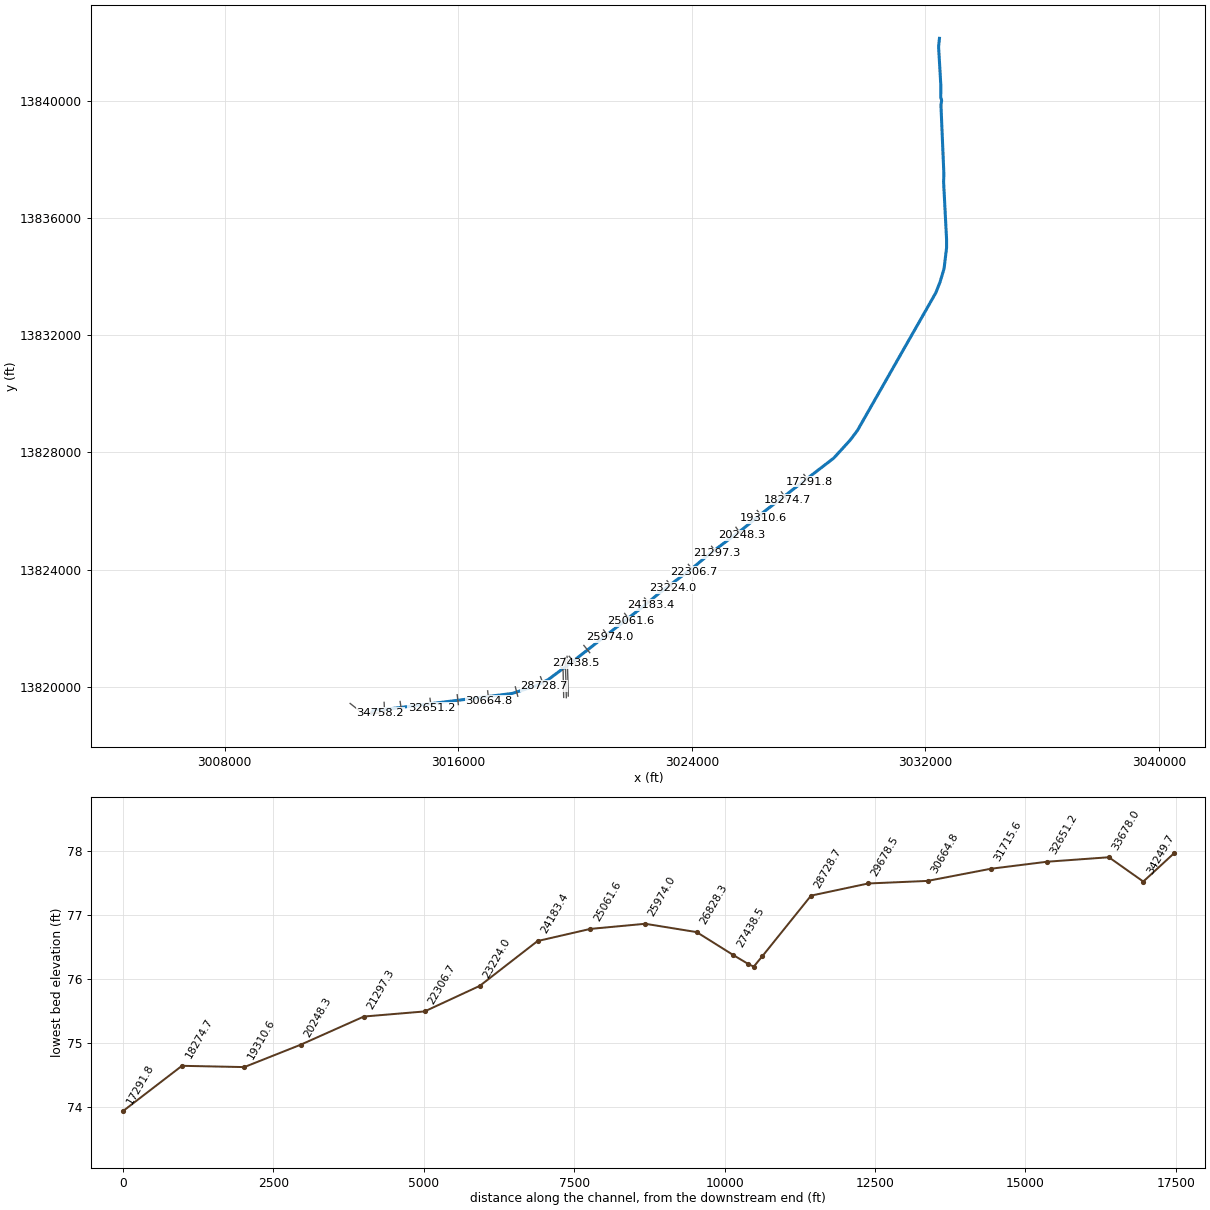
--- W190-00-00.PRJ (project) ---

Proj Title=W190-00-00
Current Plan=p03
Default Exp/Contr=.3,.1
English Units
Geom File=g01
Flow File=f01
Flow File=f03
Plan File=p01
Plan File=p03
Y Axis Title=Elevation
X Axis Title(PF)=Main Channel Distance
X Axis Title(XS)=Station
BEGIN DESCRIPTION:
Buffalo Bayou Watershed
Clodine Ditch
HCFCD Unit W190-00-00
Flood Hazard Model
10, 2, 1, 0.2% Event
Filename W190-00-00.prj
Prepared by:  Watershed Concepts  Date:
Reviewed by:                      Date:
STATUS FINAL
END DESCRIPTION:
DSS Export Rating Curves= 0
DSS Export Rating Curve Sorted= 0
DSS Export Volume Flow Curves= 0
DXF OffsetX= 0
DXF OffsetY= 0
DXF ScaleX= 1
DXF ScaleY= 10

--- W190-00-00.p03 (plan) ---

Plan Title=Floodway
Version=Version 3.0.1  Mar 2001
Short Identifier=Floodway0607
Geom File=g01
Flow File=f03
Subcritical Flow
K Sum by GR= 0
Std Step Tol= 0.01
Critical Tol= 0.01
Num of Std Step Trials= 20
Max Error Tol= 0.3
Flow Tol Ratio= 0.001
Split Flow NTrial= 30
Split Flow Tol= 0.02
Split Flow Ratio= 0.02
Log Output Level= 0
Friction Slope Method= 1
Unsteady Friction Slope Method= 2
Parabolic Critical Depth
Global Vel Dist= 0 , 0 , 0
Global Log Level= 0
CheckData=True
Encroach Param=-1 ,0,0, 2
Encroach River=W190-00-00
Encroach Reach=Reach - 1
Encroach Node=34758.2
       1  4936.6    5060
Encroach Node=34249.7
       1  4942.3    5063
Encroach Node=33678.0
       1  4934.1  5062.9
Encroach Node=32651.2
       1  4940.4  5062.8
Encroach Node=31715.6
       1  4946.9    5073
Encroach Node=30664.8
       1  4938.5    5062
Encroach Node=29678.5
       1  4936.6  5062.9
Encroach Node=28728.7
       1  4936.9  5067.4
Encroach Node=27916.5
       1  4951.5  5068.1
Encroach Node=27776.1
       1  4951.5  5068.1
Encroach Node=27732.1
       1  4951.5  5068.1
Encroach Node=27688.1
       1  4951.5  5068.1
Encroach Node=27438.5
       1  4931.2  5065.9
Encroach Node=26828.3
       1  4931.2  5065.9
Encroach Node=25974.0
       1  4932.1  5070.2
Encroach Node=25061.6
       1  4933.5  5068.6
Encroach Node=24183.4
       1  4929.1  5050.3
Encroach Node=23224.0
       1  4934.9    5067
Encroach Node=22306.7
       1  4930.8  5067.4
Encroach Node=21297.3
       1  4930.8  5066.8
Encroach Node=20248.3
       1  4931.6  5067.3
Encroach Node=19310.6
       1    4930  5066.6
Encroach Node=18274.7
       1  4927.8  5062.6
Encroach Node=17291.8
       1  4925.7  5061.5
Encroach Node=16326.9
       1  4926.6  5063.8
Encroach Node=15277.3
       1  4930.8    5068
Encroach Node=14294.8
       1  4934.1  5071.8
Encroach Node=13577.7
       1 4953.59 5072.16
Encroach Node=13395.6
       1 4953.59 5072.16
Encroach Node=13274.9
       1 4953.59 5072.16
Encroach Node=13154.2
       1 4953.59 5072.16
Encroach Node=12966.5
       1  4942.8  5078.3
Encroach Node=12672.4
       1  4942.8  5078.3
Encroach Node=11688.1
       1  4927.8  5071.3
Encroach Node=10671.1
       1  4922.5  5066.1
Encroach Node=9654.3
       1  4919.9  5069.9
Encroach Node=8649.3
       1  4917.2  5075.1
Encroach Node=7417.2
       1  4913.2  5078.1
Encroach Node=6309.9
       1  4910.5  5079.9
Encroach Node=5486.7
       1  4927.5  5081.7
Encroach Node=5391.3
       1  4927.5  5081.7
Encroach Node=5335.3
       1  4927.5  5081.7
Encroach Node=5279.3
       1  4927.5  5081.7
Encroach Node=5108.8
       1  4915.2  5079.6
Encroach Node=4798.5
       1  4915.2  5079.6
Encroach Node=3785.9
       1  4927.6  5099.4
Encroach Node=2781.9
       1  4919.2  5095.6
Encroach Node=1742.0
       1  4929.7  5088.6
Encroach Node=732.5
       1  4939.5  5083.2
Encroach Reach=W190-00-00_0007
Encroach Node=34758.2
       1  4936.6    5060
Encroach Node=34249.7
       1  4942.3    5063
Encroach Node=33678.0
       1  4934.1  5062.9
Encroach Node=32651.2
       1  4940.4  5062.8
Encroach Node=31715.6
       1  4946.9    5073
Encroach Node=30664.8
       1  4938.5    5062
Encroach Node=29678.5
       1  4936.6  5062.9
Encroach Node=28728.7
       1  4936.9  5067.4
Encroach Node=27916.5
       1  4951.5  5068.1
Encroach Node=27776.1
       1  4951.5  5068.1
Encroach Node=27732.1
       1  4951.5  5068.1
Encroach Node=27688.1
       1  4951.5  5068.1
Encroach Node=27438.5
       1  4931.2  5065.9
Encroach Node=26828.3
       1  4931.2  5065.9
Encroach Node=25974.0
       1  4932.1  5070.2
Encroach Node=25061.6
       1  4933.5  5068.6
Encroach Node=24183.4
       1  4929.1  5050.3
Encroach Node=23224.0
       1  4934.9    5067
Encroach Node=22306.7
       1  4930.8  5067.4
Encroach Node=21297.3
       1  4930.8  5066.8
Encroach Node=20248.3
       1  4931.6  5067.3
Encroach Node=19310.6
       1    4930  5066.6
Encroach Node=18274.7
       1  4927.8  5062.6
Encroach Node=17291.8
       1  4925.7  5061.5
Encroach Node=16326.9
       1  4926.6  5063.8
Encroach Node=15277.3
       1  4930.8    5068
Encroach Node=14294.8
       1  4934.1  5071.8
Encroach Node=13577.7
       1 4953.59 5072.16
Encroach Node=13395.6
       1 4953.59 5072.16
Encroach Node=13274.9
       1 4953.59 5072.16
Encroach Node=13154.2
       1 4953.59 5072.16
Encroach Node=12966.5
       1  4942.8  5078.3
Encroach Node=12672.4
       1  4942.8  5078.3
Encroach Node=11688.1
       1  4927.8  5071.3
Encroach Node=10671.1
       1  4922.5  5066.1
Encroach Node=9654.3
       1  4919.9  5069.9
Encroach Node=8649.3
       1  4917.2  5075.1
Encroach Node=7417.2
       1  4913.2  5078.1
Encroach Node=6309.9
       1  4910.5  5079.9
Encroach Node=5486.7
       1  4927.5  5081.7
Encroach Node=5391.3
       1  4927.5  5081.7
Encroach Node=5335.3
       1  4927.5  5081.7
Encroach Node=5279.3
       1  4927.5  5081.7
Encroach Node=5108.8
       1  4915.2  5079.6
Encroach Node=4798.5
       1  4915.2  5079.6
Encroach Node=3785.9
       1  4927.6  5099.4
Encroach Node=2781.9
       1  4919.2  5095.6
Encroach Node=1742.0
       1  4929.7  5088.6
Encroach Node=732.5
       1  4939.5  5083.2
Computation Interval=1HOUR
Output Interval=1HOUR
Run HTab= 0
Run UNet= 0
Run PostProcess= 0
UNET Theta= 1
UNET ZTol= 0.02
UNET ZSATol= 0.1
UNET MxIter= 20
UNET MaxInSteps= 20
UNET DtIC= 0
UNET DtMin= 0
UNET MaxCRTS= 20
UNET WFStab= 2
UNET SFStab= 1
UNET WFX= 1
UNET SFX= 1
UNET Convert EG Bridges=-1
UNET Use Existing IB Tables=-1
Instantaneous Interval=1HOUR
Write IC File= 0
IC Time=0
Write Velocity= 0
Write Detailed= 0

--- W190-00-00.p01 (plan) ---

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Plan Title=FEMA Effective June 2007
Program Version=3.13
Short Identifier=FEMAeff0607
Geom File=g01
Flow File=f01
Unsteady Bridges Friction Slope Method= 1
Encroach Param=-1 ,0,0, 0
UNET Theta Warmup= 1
UNET DSS MLevel= 4
UNET DZMax Abort= 100
UNET Froude Reduction=False
UNET Froude Limit= 1
UNET Froude Power= 10
Echo Input=False
Echo Output=False
Detailed Automatic Start=False, 10

--- W190-00-00.f03 (steady flow) ---

Flow Title=Floodway
Program Version=3.13
Number of Profiles= 2
Profile Names=1PCT_100_YR,1PCT_Floodway_100yrFW
River Rch & RM=W190-00-00,W190-00-00_0007       ,34758.2
    2259    2259
River Rch & RM=W190-00-00,W190-00-00_0007       ,25061.6
    2341    2341
River Rch & RM=W190-00-00,W190-00-00_0007       ,19310.6
    2425    2425
River Rch & RM=W190-00-00,W190-00-00_0007       ,13395.6
    2513    2513
River Rch & RM=W190-00-00,W190-00-00_0007       ,3785.9
    2651    2651
River Rch & RM=W190-00-00,W190-00-00_0007       ,1742
    2696    2696
Boundary for River Rch & Prof#=W190-00-00,W190-00-00_0007       , 1
Up Type= 0
Dn Type= 3
Dn Slope=0.00023
Boundary for River Rch & Prof#=W190-00-00,W190-00-00_0007       , 2
Up Type= 0
Dn Type= 1
Dn Known WS=78.62
DSS Import GetInterval= 0
DSS Import GetPeak= 0
DSS Import FillOption= 0

--- W190-00-00.f01 (steady flow) ---

Flow Title=FEMA Effective June 2007
Program Version=3.13
Number of Profiles= 4
Profile Names=10PCT_10yr,2PCT_50yr,1PCT_100yr,0.2PCT_500yr
River Rch & RM=W190-00-00,W190-00-00_0007 ,34758.2
    1034    1800    2259    3726
River Rch & RM=W190-00-00,W190-00-00_0007 ,25061.6
    1068    1864    2341    3856
River Rch & RM=W190-00-00,W190-00-00_0007 ,19310.6
    1102    1928    2425    3989
River Rch & RM=W190-00-00,W190-00-00_0007 ,13395.6
    1139    1997    2513    4129
River Rch & RM=W190-00-00,W190-00-00_0007 ,3785.9
    1196    2103    2651    4348
River Rch & RM=W190-00-00,W190-00-00_0007 ,1742
    1215    2138    2696    4419
Boundary for River Rch & Prof#=W190-00-00,W190-00-00_0007 , 1
Up Type= 0
Dn Type= 3
Dn Slope=0.00023
Boundary for River Rch & Prof#=W190-00-00,W190-00-00_0007 , 2
Up Type= 0
Dn Type= 3
Dn Slope=0.00023
Boundary for River Rch & Prof#=W190-00-00,W190-00-00_0007 , 3
Up Type= 0
Dn Type= 3
Dn Slope=0.00023
Boundary for River Rch & Prof#=W190-00-00,W190-00-00_0007 , 4
Up Type= 0
Dn Type= 3
Dn Slope=0.00023
DSS Import GetInterval= 0
DSS Import GetPeak= 0
DSS Import FillOption= 0

--- W190-00-00.g01 (geometry) ---

Geom Title=W190-00-00 June 2007
Version=Version 3.0.1  Mar 2001

River Reach=W190-00-00      ,W190-00-00_0007
Reach XY= 30
      3013019.72     13819087.92      3013085.75       13819181.
      3013169.75       13819209.      3013617.25       13819237.
        3017837.       13819765.      3018646.25       13820023.
      3019086.25       13820244.      3020003.25       13820923.
      3022392.25       13822782.      3022882.25       13823193.
        3024072.       13824086.      3024588.25       13824519.
      3025772.25       13825402.      3026323.25       13825858.
      3028861.75       13827804.        3029427.       13828421.
        3029679.       13828757.      3032359.38     13833452.04
      3032503.34     13833816.02      3032641.87     13834275.08
      3032728.25       13834992.      3032728.25       13835272.
      3032625.58     13837254.88       3032636.5       13837495.
      3032535.25       13839865.       3032559.5       13840020.
      3032528.25       13840134.      3032533.25       13840506.
      3032454.45     13841859.04      3032484.33     13842144.25

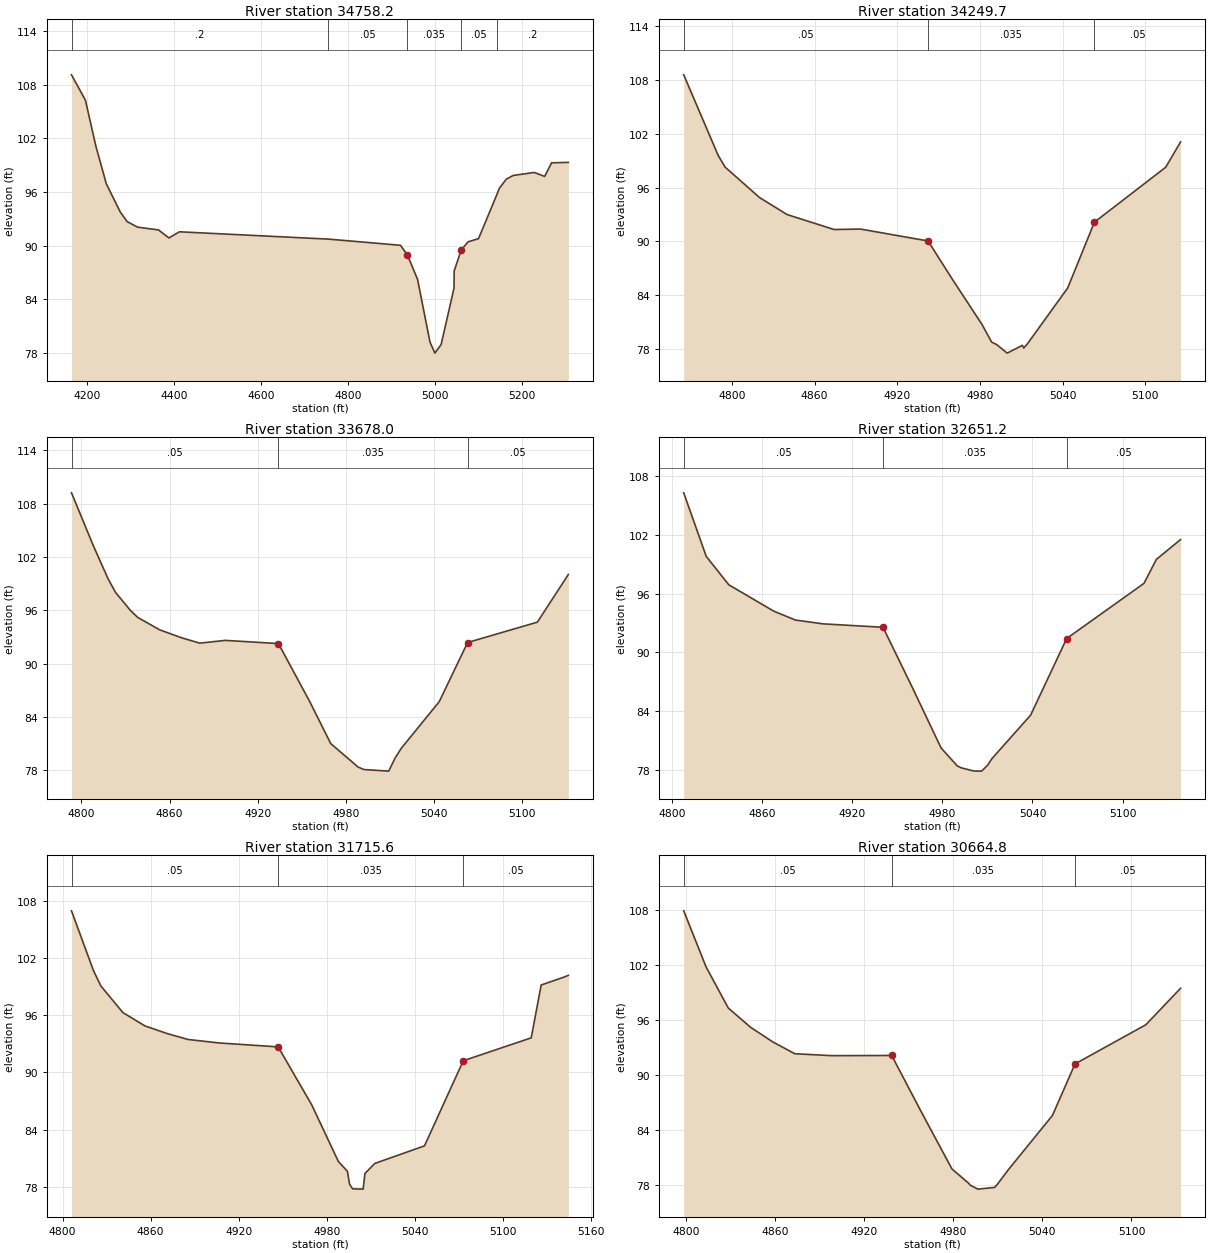
Type RM Length L Ch R = 1 ,34758.2 ,687.3,508.5,430.8
BEGIN DESCRIPTION:
Cross Section 34758.2-Interpolated
END DESCRIPTION:
XS GIS Cut Line= 5
      3012295.85     13819425.83      3012700.96      13819105.6
      3012990.32     13819086.31      3013063.63     13819090.17
      3013325.98     13819097.89
#Sta/Elev= 30
  4164.2  109.12  4196.2  106.28  4220.2  101.14  4244.2   96.93  4276.2   93.77
  4292.2   92.69  4316.2   92.07  4364.2   91.76  4388.2   90.86  4412.2   91.55
    4755   90.73  4920.6   90.04  4936.6   88.94  4959.9   86.22  4988.4    79.2
  4999.7   77.97    5014   78.93  5043.6   85.24    5044   87.16    5060    89.5
    5076   90.43    5100   90.78  5141.6   95.65    5148   96.43    5164   97.45
    5180   97.86    5228   98.19    5252   97.75    5268   99.27  5306.5   99.32
#Mann= 5 , 1 , 0
  4164.2      .2       0    4755     .05       0  4936.6    .035       0
    5060     .05       0  5141.6      .2       0
Bank Sta=4936.6,5060
XS Rating Curve= 0
Exp/Cntr=.3,.1

Type RM Length L Ch R = 1 ,34249.7 ,564.5,571.7,577.8
BEGIN DESCRIPTION:
Cross Section 34249.7
END DESCRIPTION:
XS GIS Cut Line= 2
      3013460.63     13819462.62      3013476.17     13819102.45
#Sta/Elev= 20
    4765   108.6    4790    99.6    4795    98.3    4820    94.9    4840      93
  4874.1   91.33  4893.3   91.38  4942.3   90.05  4959.9   85.78  4981.5   80.71
  4988.4   78.76    4992   78.49  4999.7   77.53  5010.7    78.4  5011.7    78.1
    5014   78.49  5043.6    84.8    5063   92.15  5114.7   98.28  5125.5  101.11
#Mann= 3 , 1 , 0
    4765     .05       0  4942.3    .035       0    5063     .05       0
Bank Sta=4942.3,5063
XS Rating Curve= 0
Exp/Cntr=.3,.1

Type RM Length L Ch R = 1 ,33678.0 ,1027.2,1026.8,1026.5
BEGIN DESCRIPTION:
Cross Section 33678.0
END DESCRIPTION:
XS GIS Cut Line= 2
      3014008.57     13819492.35      3014058.51     13819157.76
#Sta/Elev= 23
  4793.2   109.2  4808.2   103.2  4818.2    99.5  4823.2      98  4833.2      96
  4838.2    95.2  4853.2    93.8  4868.2    92.9  4880.5    92.3    4898   92.61
  4934.1   92.25  4955.5    85.7  4969.7   81.01  4986.5   78.63  4988.2   78.38
  4992.3   78.09  5009.2   77.91  5013.6    79.4  5017.8   80.49  5043.6   85.72
  5062.9   92.37  5110.4   94.66  5131.5  100.02
#Mann= 3 , 1 , 0
  4793.2     .05       0  4934.1    .035       0  5062.9     .05       0
Bank Sta=4934.1,5062.9
XS Rating Curve= 0
Exp/Cntr=.3,.1

Type RM Length L Ch R = 1 ,32651.2 ,937.1,935.6,934.1
BEGIN DESCRIPTION:
Cross Section 32651.2
END DESCRIPTION:
XS GIS Cut Line= 2
      3015031.13     13819600.17      3015078.52     13819272.48
#Sta/Elev= 20
  4807.6   106.3  4822.6    99.8  4837.6    96.9  4867.6    94.2    4882   93.29
  4900.5    92.9  4940.4   92.55  4959.8   86.44  4979.1   80.21  4989.9   78.37
  4992.5   78.18  5000.9   77.85  5006.1   77.84  5010.1   78.44    5013   79.12
  5038.8   83.57  5062.8    91.4  5114.3   97.04  5122.6    99.5  5138.7  101.52
#Mann= 3 , 1 , 0
  4807.6     .05       0  4940.4    .035       0  5062.8     .05       0
Bank Sta=4940.4,5062.8
XS Rating Curve= 0
Exp/Cntr=.3,.1

Type RM Length L Ch R = 1 ,31715.6 ,1051.3,1050.8,1050.8
BEGIN DESCRIPTION:
Cross Section 31715.6
END DESCRIPTION:
XS GIS Cut Line= 2
      3015963.63     13819722.89       3016003.3     13819386.73
#Sta/Elev= 23
  4806.1     107  4821.1   100.7  4826.1    99.1  4841.1    96.3  4856.1    94.9
  4871.1    94.1  4885.5   93.47  4906.9    93.1  4946.9   92.69  4969.8   86.58
  4987.9   80.64  4994.1    79.6  4995.5   78.27  4997.6   77.76  5004.8   77.73
    5006   79.37  5012.7   80.43  5046.6   82.28    5073   91.23  5119.3   93.64
  5126.1    99.2  5141.1     100  5144.6  100.21
#Mann= 3 , 1 , 0
  4806.1     .05       0  4946.9    .035       0    5073     .05       0
Bank Sta=4946.9,5073
XS Rating Curve= 0
Exp/Cntr=.3,.1

Type RM Length L Ch R = 1 ,30664.8 ,976.1,986.3,994.6
BEGIN DESCRIPTION:
Cross Section 30664.8
END DESCRIPTION:
XS GIS Cut Line= 2
      3017006.82     13819855.68      3017044.88     13819523.16
#Sta/Elev= 20
  4798.4   107.9  4813.4   101.8  4828.4    97.3  4843.4    95.2  4858.4    93.6
  4873.2   92.31  4898.2    92.1  4938.5   92.12  4958.1   86.07  4979.1   79.74
  4990.2    78.2  4991.5   77.96  4996.6   77.54  5007.9   77.73  5009.9   78.11
  5016.6   79.56  5046.8   85.58    5062    91.2  5109.7   95.47  5133.1   99.45
#Mann= 3 , 1 , 0
  4798.4     .05       0  4938.5    .035       0    5062     .05       0
Bank Sta=4938.5,5062
XS Rating Curve= 0
Exp/Cntr=.3,.1

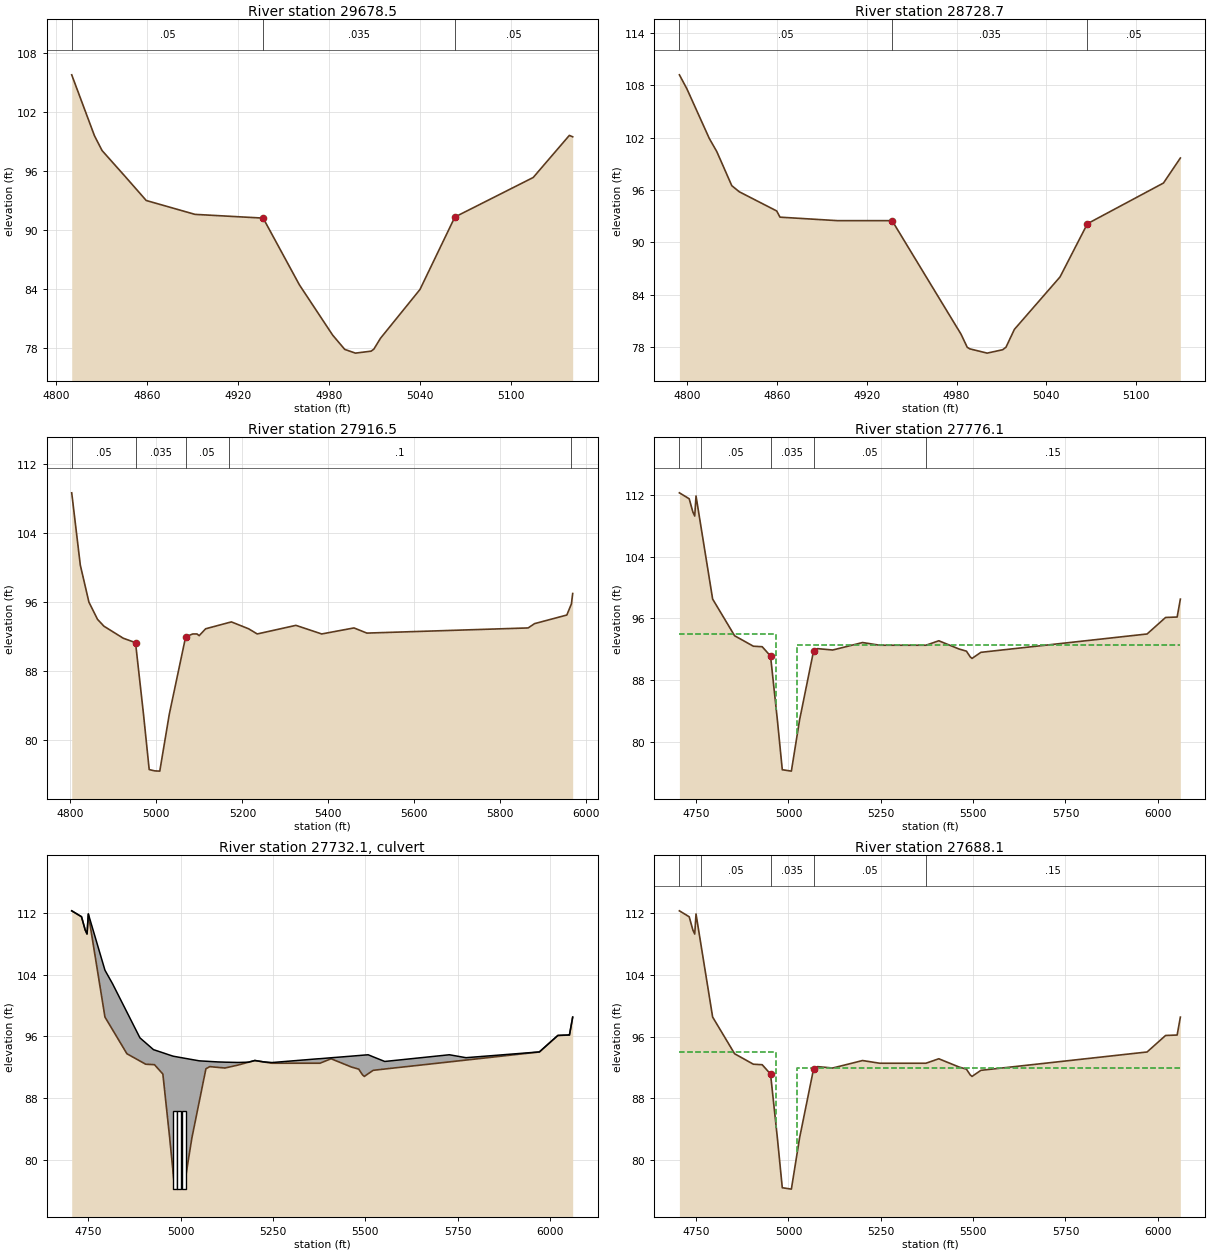
Type RM Length L Ch R = 1 ,29678.5 ,942.5,949.8,955.2
BEGIN DESCRIPTION:
Cross Section 29678.5
END DESCRIPTION:
XS GIS Cut Line= 2
      3017955.13       13819992.      3018038.43     13819672.68
#Sta/Elev= 20
  4810.5   105.8  4825.5    99.6  4830.5    98.1  4845.5    95.5  4859.6   93.02
  4891.7   91.61  4936.6   91.23  4960.5   84.44  4982.4   79.33  4990.4   77.87
  4990.7   77.86  4997.4    77.5  5007.7    77.7  5009.5    77.9  5013.9   79.01
  5039.9   83.97  5062.9   91.34  5114.5   95.36  5138.3   99.64  5140.5    99.5
#Mann= 3 , 1 , 0
  4810.5     .05       0  4936.6    .035       0  5062.9     .05       0
Bank Sta=4936.6,5062.9
XS Rating Curve= 0
Exp/Cntr=.3,.1

Type RM Length L Ch R = 1 ,28728.7 ,801.8,812.2,822.4
BEGIN DESCRIPTION:
Cross Section 28728.7
END DESCRIPTION:
XS GIS Cut Line= 3
      3018818.29     13820337.51      3018931.48      13820027.3
      3018931.74     13820022.82
#Sta/Elev= 22
  4794.8   109.2  4799.8   107.6  4814.8   101.9  4819.8   100.4  4829.8    96.5
  4834.8    95.8  4859.8    93.6    4862   92.89  4900.4   92.49  4936.9   92.49
  4962.2   85.34    4983   79.47  4987.1   77.98  4988.8    77.8  5000.4   77.31
  5010.8    77.7    5013   77.99  5018.6   80.03  5049.1   86.04  5067.4   92.14
  5118.2    96.8  5129.5   99.67
#Mann= 3 , 1 , 0
  4794.8     .05       0  4936.9    .035       0  5067.4     .05       0
Bank Sta=4936.9,5067.4
XS Rating Curve= 0
Exp/Cntr=.3,.1

Type RM Length L Ch R = 1 ,27916.5 ,147.7,140.4,76.6
BEGIN DESCRIPTION:
Cross Section 27916.5-Interpolated
END DESCRIPTION:
XS GIS Cut Line= 4
      3019453.96     13820755.94      3019531.06     13820651.62
      3019591.76     13820540.34      3019612.05     13819632.04
#Sta/Elev= 30
  4803.1   108.7  4823.1   100.3  4843.1      96  4863.1      94  4878.1    93.2
  4923.1    91.8  4951.5   91.29    4970   82.99  4983.3   76.54  4996.1   76.39
  5007.9   76.36    5030   82.97  5068.1   91.97  5084.5    92.3  5094.5    92.3
  5099.5    92.1  5114.5    92.9  5168.3   93.62  5174.5    93.7  5214.5    92.9
  5234.5    92.3  5324.5    93.3  5384.5    92.3  5459.5      93  5489.5    92.4
  5864.5      93  5879.5    93.5  5954.5    94.5  5965.2    95.8  5968.1      97
#Mann= 5 , 1 , 0
  4803.1     .05       0  4951.5    .035       0  5068.1     .05       0
  5168.3      .1       0  5965.2      .2       0
Bank Sta=4951.5,5068.1
XS Rating Curve= 0
Exp/Cntr=.5,.3

Type RM Length L Ch R = 1 ,27776.1 ,88,88,88
BEGIN DESCRIPTION:
Upstream Section of Bridge/Culvert/Weir
END DESCRIPTION:
XS GIS Cut Line= 3
      3019660.42     13820977.91        3019688.     13820205.77
      3019701.97     13819622.07
#Sta/Elev= 30
  4704.7   112.3  4731.2  111.53  4741.2  109.81  4746.2  109.29  4749.7  111.89
  4794.7   98.52  4854.2   93.76  4905.1    92.4  4928.8   92.34  4951.5   91.13
    4970   82.83  4983.3   76.38  5007.9    76.2    5030   82.81  5068.1   91.81
  5078.7   92.09  5119.8   91.91  5200.6   92.88    5247   92.53  5372.3   92.53
    5407   93.11    5462   92.04    5482   91.76    5492   91.03    5497   90.82
  5521.1   91.61  5971.1   93.99  6021.1   96.13  6052.5   96.19  6061.2   98.51
#Mann= 5 , 1 , 0
  4704.7      .2       0  4763.2     .05       0  4951.5    .035       0
  5068.1     .05       0  5372.3     .15       0
#XS Ineff= 2 , 0
       0    4967      94    5024       0    92.6
Permanent Ineff=
       F       F
Bank Sta=4951.5,5068.1
XS Rating Curve= 0
Exp/Cntr=.5,.3

Type RM Length L Ch R = 2 ,27732.1 ,,,
BEGIN DESCRIPTION:
BARKER CLODINE ROAD, SKEW ANGLE OF 35 DEGREES
Structure ID: W90-6
END DESCRIPTION:
Bridge Culvert--1,0,-1,-1, 0
Deck Dist Width WeirC Skew NumUp NumDn MinLoCord MaxHiCord MaxSubmerge Is_Ogee
10,68,3,0, 53, 53, , , .95, 0, 1,1,,
  4704.7 4708.79  4708.9 4709.01  4731.2  4741.2  4746.2  4749.7  4794.7  4815.3
  4854.2  4889.5  4905.1  4926.2  4928.8  4951.5    4970    4979  4983.3  4996.1
  5007.9    5030  5050.5  5068.1  5078.7  5100.8  5119.8  5155.7 5183.29  5183.4
 5183.51  5200.6  5223.9    5247  5372.3    5377    5407    5462    5482    5492
    5497  5507.3  5521.1  5552.3  5727.3  5772.3  5971.1  5992.3  6021.1  6022.3
  6052.3  6052.5  6061.2
  112.29  112.18  112.18  112.17  111.53  109.81  109.29  111.89  104.59  102.83
   99.15   95.81   95.16   94.28   94.24   93.88   93.58   93.44    93.4   93.29
   93.19      93   92.83   92.78   92.75   92.69   92.66   92.62   92.66   92.66
   92.66   92.88    92.7   92.61    93.1   93.11   93.23   93.44   93.52   93.56
   93.58   93.62   93.35   92.75   93.62   93.24   93.99    94.9   96.13   96.13
   96.19   96.18    98.5
  112.29  112.17  112.17  112.16  111.52   109.8  109.28  111.88   98.51   96.86
   93.75   92.81   92.39   92.34   92.33   91.12   82.82   78.46   76.37   76.22
   76.19    82.8   87.64    91.8   92.08   91.98    91.9   92.29   92.65   92.65
   92.65   92.87   92.69   92.52   92.52   92.52    93.1   92.03   91.75   91.02
   90.81   91.15    91.6   91.77   92.69   92.93   93.98   94.89   96.12   96.12
   96.18   96.18    98.5
  4704.7 4708.79  4708.9 4709.01  4731.2  4741.2  4746.2  4749.7  4794.7  4815.3
  4854.2  4889.5  4905.1  4926.2  4928.8  4951.5    4970    4979  4983.3  4996.1
  5007.9    5030  5050.5  5068.1  5078.7  5100.8  5119.8  5155.7 5183.29  5183.4
 5183.51  5200.6  5223.9    5247  5372.3    5377    5407    5462    5482    5492
    5497  5507.3  5521.1  5552.3  5727.3  5772.3  5971.1  5992.3  6021.1  6022.3
  6052.3  6052.5  6061.2
  112.33  112.21  112.21   112.2  111.56  109.84  109.32  111.92  104.59  102.83
   99.15   95.81   95.16   94.28   94.24   93.88   93.58   93.44    93.4   93.29
   93.19      93   92.83   92.78   92.75   92.69   92.66   92.62   92.69   92.69
   92.69   92.91   92.73   92.61    93.1   93.11   93.23   93.44   93.52   93.56
   93.58   93.62   93.35   92.75   93.62   93.24   94.02   94.93   96.16   96.16
   96.22   96.22   98.54
  112.33  112.21  112.21   112.2  111.56  109.84  109.32  111.92   98.55    96.9
   93.79   92.85   92.43   92.38   92.37   91.16   82.86    78.5   76.41   76.26
   76.23   82.84   87.68   91.84   92.12   92.02   91.94   92.33   92.69   92.69
   92.69   92.91   92.73   92.56   92.56   92.56   93.14   92.07   91.79   91.06
   90.85   91.19   91.64   91.81   92.73   92.97   94.02   94.93   96.16   96.16
   96.22   96.22   98.54
BR Coef= 1 , 0 , 0 ,1.25, 0 ,,,.8,-1,2,0,
WSPro=,,,, 1 ,,,, 0 ,,,, 0 ,,,,-1 ,-1 ,-1 , 0 , 0 , 0 , 0 , 0
Culvert=2,10.1,11.3,68,.015,.4,1,8,1,76.19,4983.3,76.2,4983.3,Culvert #1  , 0 ,10
Culvert Bottom n=.015
Culvert=2,10.1,11.3,68,.015,.4,1,8,1,76.19,4996.1,76.2,4996.1,Culvert #2  , 0 ,10
Culvert Bottom n=.015
Culvert=2,10.1,11.3,68,.015,.4,1,8,1,76.19,5007.9,76.2,5007.9,Culvert #3  , 0 ,10
Culvert Bottom n=.015
BR U #Sta/Elev= 53
  4704.7  112.29 4708.79  112.17  4708.9  112.17 4709.01  112.16  4731.2  111.52
  4741.2   109.8  4746.2  109.28  4749.7  111.88  4794.7   98.51  4815.3   96.86
  4854.2   93.75  4889.5   92.81  4905.1   92.39  4926.2   92.34  4928.8   92.33
  4951.5   91.12    4970   82.82    4979   78.46  4983.3   76.37  4996.1   76.22
  5007.9   76.19    5030    82.8  5050.5   87.64  5068.1    91.8  5078.7   92.08
  5100.8   91.98  5119.8    91.9  5155.7   92.29 5183.29   92.65  5183.4   92.65
 5183.51   92.65  5200.6   92.87  5223.9   92.69    5247   92.52  5372.3   92.52
    5377   92.52    5407    93.1    5462   92.03    5482   91.75    5492   91.02
    5497   90.81  5507.3   91.15  5521.1    91.6  5552.3   91.77  5727.3   92.69
  5772.3   92.93  5971.1   93.98  5992.3   94.89  6021.1   96.12  6022.3   96.12
  6052.3   96.18  6052.5   96.18  6061.2    98.5
BR U #Mann= 5
  4704.7      .2  4763.2     .05  4951.5    .035  5068.1     .05  5372.3     .15
BR U Banks=4951.5,5068.1
BR D #Sta/Elev= 53
  4704.7  112.33 4708.79  112.21  4708.9  112.21 4709.01   112.2  4731.2  111.56
  4741.2  109.84  4746.2  109.32  4749.7  111.92  4794.7   98.55  4815.3    96.9
  4854.2   93.79  4889.5   92.85  4905.1   92.43  4926.2   92.38  4928.8   92.37
  4951.5   91.16    4970   82.86    4979    78.5  4983.3   76.41  4996.1   76.26
  5007.9   76.23    5030   82.84  5050.5   87.68  5068.1   91.84  5078.7   92.12
  5100.8   92.02  5119.8   91.94  5155.7   92.33 5183.29   92.69  5183.4   92.69
 5183.51   92.69  5200.6   92.91  5223.9   92.73    5247   92.56  5372.3   92.56
    5377   92.56    5407   93.14    5462   92.07    5482   91.79    5492   91.06
    5497   90.85  5507.3   91.19  5521.1   91.64  5552.3   91.81  5727.3   92.73
  5772.3   92.97  5971.1   94.02  5992.3   94.93  6021.1   96.16  6022.3   96.16
  6052.3   96.22  6052.5   96.22  6061.2   98.54
BR D #Mann= 5
  4704.7      .2  4763.2     .05  4951.5    .035  5068.1     .05  5372.3     .15
BR D Banks=4951.5,5068.1
BC Design=,, 0 ,, 0 ,,,,,,
BC HTab HWMax=112.3

Type RM Length L Ch R = 1 ,27688.1 ,249.6,249.6,249.6
BEGIN DESCRIPTION:
Downstream Section of Bridge/Culvert/Weir
END DESCRIPTION:
XS GIS Cut Line= 3
      3019727.91     13821034.39      3019755.48     13820262.25
      3019769.46     13819678.54
#Sta/Elev= 30
  4704.7  112.34  4731.2  111.57  4741.2  109.85  4746.2  109.33  4749.7  111.93
  4794.7   98.56  4854.2    93.8  4905.1   92.44  4928.8   92.38  4951.5   91.17
    4970   82.87  4983.3   76.42  5007.9   76.24    5030   82.85  5068.1   91.85
  5078.7   92.13  5119.8   91.95  5200.6   92.92    5247   92.57  5372.3   92.57
    5407   93.15    5462   92.08    5482    91.8    5492   91.07    5497   90.86
  5521.1   91.65  5971.1   94.03  6021.1   96.17  6052.5   96.23  6061.2   98.55
#Mann= 5 , 1 , 0
  4704.7      .2       0  4763.2     .05       0  4951.5    .035       0
  5068.1     .05       0  5372.3     .15       0
#XS Ineff= 2 , 0
       0    4967      94    5024       0      92
Permanent Ineff=
       F       F
Bank Sta=4951.5,5068.1
XS Rating Curve= 0
Exp/Cntr=.5,.3

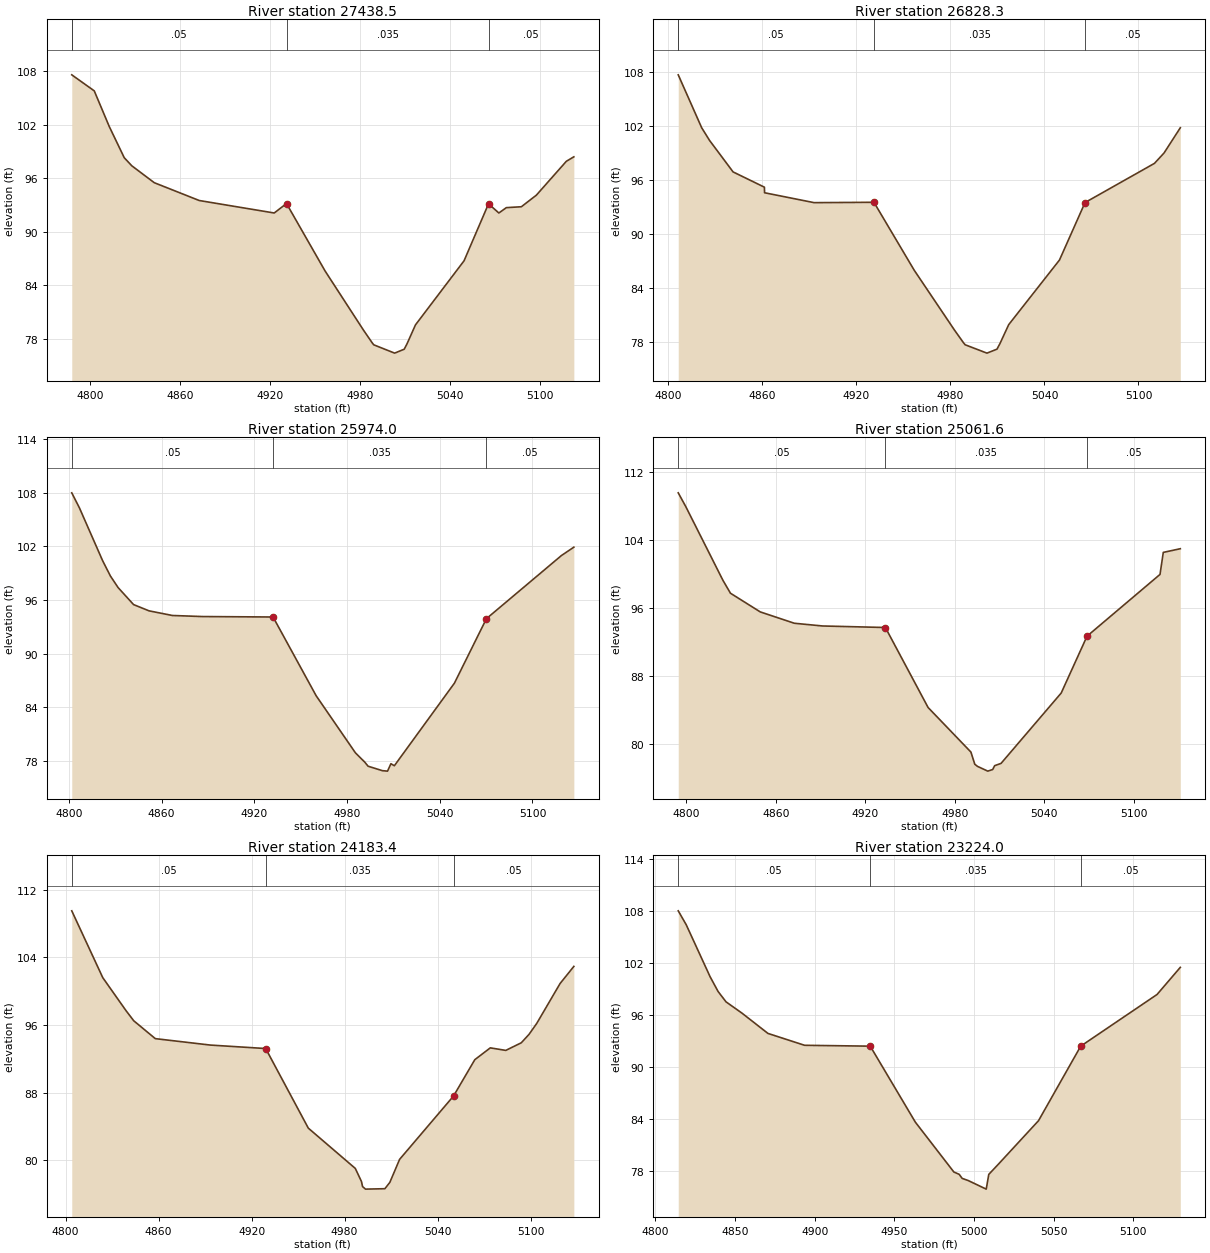
Type RM Length L Ch R = 1 ,27438.5 ,616.7,610.2,603.6
BEGIN DESCRIPTION:
Cross Section 27438.5-Interpolated
END DESCRIPTION:
XS GIS Cut Line= 4
      3019799.14     13821036.04      3019905.36     13820919.71
      3019981.24     13820843.83      3020030.69     13820794.38
#Sta/Elev= 25
    4788   107.6    4803   105.8    4813   101.8    4823    98.3    4828    97.4
    4843    95.5    4873    93.5    4923    92.1  4931.2   93.16  4956.9    85.6
  4982.6   78.94  4988.4   77.52  4989.4   77.31  5003.3   76.38  5009.7   76.82
  5011.6   77.44  5017.2   79.55  5049.6   86.74  5065.9   93.13  5072.8    92.1
  5077.8    92.7  5087.8    92.8  5097.8    94.1  5117.8    97.9  5122.8    98.4
#Mann= 4 , 1 , 0
    4788      .2       0    4788     .05       0  4931.2    .035       0
  5065.9     .05       0
Bank Sta=4931.2,5065.9
XS Rating Curve= 0
Exp/Cntr=.3,.1

Type RM Length L Ch R = 1 ,26828.3 ,855.3,854.3,853.6
BEGIN DESCRIPTION:
Cross Section 26828.3
END DESCRIPTION:
XS GIS Cut Line= 2
      3020302.52      13821407.3      3020504.44     13821158.51
#Sta/Elev= 21
  4806.3   107.7  4821.3   101.8  4826.3   100.4  4841.3    96.9  4861.3    95.2
  4861.4   94.58    4893   93.48  4931.2   93.52  4956.9   85.96  4982.6    79.3
  4988.4   77.88  4989.4   77.67  5003.3   76.74  5009.7   77.18  5011.6    77.8
  5017.2   79.91  5049.6    87.1  5065.9   93.49  5110.2   97.85  5116.3      99
  5126.7  101.81
#Mann= 4 , 1 , 0
  4806.3      .2       0  4806.3     .05       0  4931.2    .035       0
  5065.9     .05       0
Bank Sta=4931.2,5065.9
XS Rating Curve= 0
Exp/Cntr=.3,.1

Type RM Length L Ch R = 1 ,25974.0 ,914.1,912.4,910.9
BEGIN DESCRIPTION:
Cross Section 25974.0
END DESCRIPTION:
XS GIS Cut Line= 2
       3020977.8     13821935.31      3021178.75     13821679.88
#Sta/Elev= 22
  4801.8     108  4806.8   106.3  4821.8   100.4  4826.8    98.7  4831.8    97.4
  4841.8    95.5  4851.8    94.8  4866.9   94.28  4886.4   94.16  4932.1   94.11
    4960    85.3  4985.4   78.92  4991.5   77.87  4993.6   77.42  5002.9   76.92
  5006.2   76.87  5008.4    77.7  5010.6   77.47  5049.5   86.71  5070.2   93.92
  5118.8  100.99  5126.8  101.92
#Mann= 3 , 1 , 0
  4801.8     .05       0  4932.1    .035       0  5070.2     .05       0
Bank Sta=4932.1,5070.2
XS Rating Curve= 0
Exp/Cntr=.3,.1

Type RM Length L Ch R = 1 ,25061.6 ,872.3,878.2,882.7
BEGIN DESCRIPTION:
Cross Section 25061.6
END DESCRIPTION:
XS GIS Cut Line= 2
      3021699.65     13822501.71      3021900.88     13822232.14
#Sta/Elev= 21
  4794.7   109.5  4799.7   107.9  4824.7    99.2  4829.7    97.7  4849.7    95.5
  4872.5   94.17  4891.4   93.85  4933.5   93.67  4962.1   84.27  4990.8   79.03
  4993.4    77.6  4995.2   77.35  5002.1   76.79  5005.4   76.98  5006.7   77.43
    5011    77.7  5051.3   85.97  5068.6   92.65  5117.5   99.91  5119.7   102.5
  5131.1  102.93
#Mann= 3 , 1 , 0
  4794.7     .05       0  4933.5    .035       0  5068.6     .05       0
Bank Sta=4933.5,5068.6
XS Rating Curve= 0
Exp/Cntr=.3,.1

Type RM Length L Ch R = 1 ,24183.4 ,962.6,959.4,956.3
BEGIN DESCRIPTION:
Cross Section 24183.4
END DESCRIPTION:
XS GIS Cut Line= 2
      3022381.08     13823028.34      3022596.27     13822786.26
#Sta/Elev= 24
    4804   109.5    4824   101.6    4839    97.7    4844    96.5  4857.9   94.39
  4893.4   93.63  4929.1   93.22  4956.6   83.81  4986.9   79.05  4990.9    77.5
  4991.6    76.9  4993.5    76.6    5006   76.65  5009.2    77.4  5015.5   80.12
  5050.3   87.61    5064    91.9    5074    93.3    5084      93    5094    93.9
    5099    94.9    5104    96.2    5119   100.9  5127.9  102.93
#Mann= 3 , 1 , 0
    4804     .05       0  4929.1    .035       0  5050.3     .05       0
Bank Sta=4929.1,5050.3
XS Rating Curve= 0
Exp/Cntr=.3,.1

Type RM Length L Ch R = 1 ,23224.0 ,918.7,917.3,916.5
BEGIN DESCRIPTION:
Cross Section 23224.0
END DESCRIPTION:
XS GIS Cut Line= 2
      3023151.44     13823616.41      3023348.28     13823370.36
#Sta/Elev= 21
  4814.4     108  4819.4   106.4  4834.4   100.4  4839.4    98.7  4844.4    97.5
  4854.4    96.2  4870.7   93.86  4893.7   92.49  4934.9   92.39  4963.2   83.63
  4987.4   77.87  4990.7   77.61  4992.6   77.14  4996.5   76.88  5007.7    75.9
  5009.3    77.6  5015.7   78.85  5040.5   83.79    5067   92.39  5114.9   98.35
  5129.5  101.48
#Mann= 3 , 1 , 0
  4814.4     .05       0  4934.9    .035       0    5067     .05       0
Bank Sta=4934.9,5067
XS Rating Curve= 0
Exp/Cntr=.3,.1

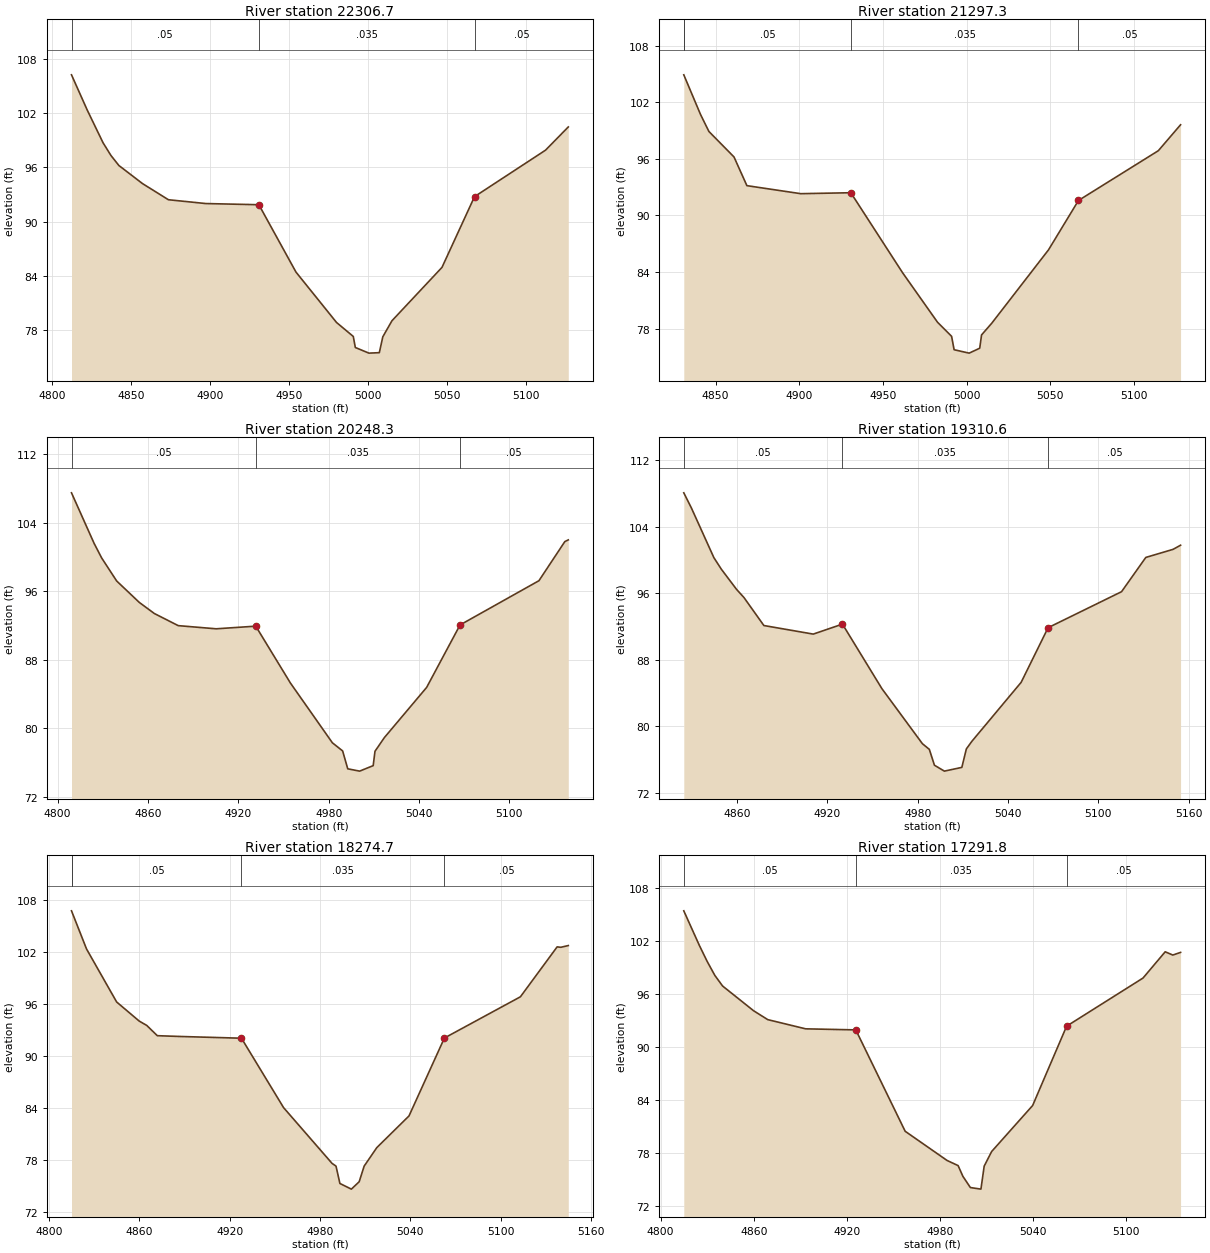
Type RM Length L Ch R = 1 ,22306.7 ,1008.3,1009.4,1009.7
BEGIN DESCRIPTION:
Cross Section 22306.7
END DESCRIPTION:
XS GIS Cut Line= 2
      3023881.52     13824176.33      3024074.24     13823927.54
#Sta/Elev= 21
  4812.1   106.2  4822.1   102.3  4832.1    98.7  4837.1    97.3  4842.1    96.2
  4857.1    94.2  4873.5   92.42  4897.2      92  4930.8   91.87  4954.3   84.44
    4980   78.88  4990.6   77.34  4991.9   76.12  5000.5    75.5  5007.1   75.55
  5009.3    77.3  5015.1   79.07  5046.8   84.96  5067.4   92.76  5112.4   97.89
  5126.8  100.45
#Mann= 3 , 1 , 0
  4812.1     .05       0  4930.8    .035       0  5067.4     .05       0
Bank Sta=4930.8,5067.4
XS Rating Curve= 0
Exp/Cntr=.3,.1

Type RM Length L Ch R = 1 ,21297.3 ,1052.7,1049,1046.2
BEGIN DESCRIPTION:
Cross Section 21297.3
END DESCRIPTION:
XS GIS Cut Line= 2
       3024678.4      13824792.8      3024861.94     13824559.55
#Sta/Elev= 19
    4831   104.9    4841   100.7    4846    98.9    4861    96.2  4868.7   93.16
  4900.9   92.31  4930.8   92.41  4961.7   83.94  4982.6   78.69    4991    77.2
  4992.5   75.78  5001.5   75.42  5007.8   75.94  5008.9   77.35    5015   78.59
  5048.9   86.36  5066.8   91.59  5114.5   96.86  5127.8   99.61
#Mann= 4 , 1 , 0
    4831      .2       0    4831     .05       0  4930.8    .035       0
  5066.8     .05       0
Bank Sta=4930.8,5066.8
XS Rating Curve= 0
Exp/Cntr=.3,.1

Type RM Length L Ch R = 1 ,20248.3 ,933.1,937.7,941.9
BEGIN DESCRIPTION:
Cross Section 20248.3
END DESCRIPTION:
XS GIS Cut Line= 2
      3025512.92     13825443.54      3025703.67     13825174.25
#Sta/Elev= 22
  4809.2   107.5  4824.2   101.6  4829.2    99.9  4839.2    97.2  4854.2    94.7
  4864.2    93.4  4880.1   91.98  4905.3   91.61  4931.6   91.92  4954.6   85.28
  4982.5   78.29  4989.3   77.34  4992.7   75.25  5000.6   74.98  5009.6   75.62
  5010.8    77.3    5017   78.89  5045.1   84.76  5067.3   92.06  5119.7   97.23
  5136.9   101.8  5139.2     102
#Mann= 3 , 1 , 0
  4809.2     .05       0  4931.6    .035       0  5067.3     .05       0
Bank Sta=4931.6,5067.3
XS Rating Curve= 0
Exp/Cntr=.3,.1

Type RM Length L Ch R = 1 ,19310.6 ,1039.5,1035.9,1034.8
BEGIN DESCRIPTION:
Cross Section 19310.6
END DESCRIPTION:
XS GIS Cut Line= 2
      3026241.71     13826015.89      3026447.41     13825757.84
#Sta/Elev= 23
  4824.6   108.1  4829.6   106.3  4844.6   100.3  4849.6    98.9  4859.6    96.5
  4864.6    95.5  4877.8   92.14  4910.6   91.11    4930   92.31  4956.2   84.55
  4983.1   77.93  4987.7   77.25  4991.1   75.34  4997.7   74.63  5009.3   75.08
  5012.3    77.3  5015.9    78.2  5048.7   85.31  5066.6   91.88  5115.4   96.21
  5131.5  100.33  5149.6   101.3  5154.6   101.8
#Mann= 3 , 1 , 0
  4824.6     .05       0    4930    .035       0  5066.6     .05       0
Bank Sta=4930,5066.6
XS Rating Curve= 0
Exp/Cntr=.3,.1

Type RM Length L Ch R = 1 ,18274.7 ,979.1,982.9,986
BEGIN DESCRIPTION:
Cross Section 18274.7
END DESCRIPTION:
XS GIS Cut Line= 2
      3027069.38     13826653.38       3027262.3     13826385.66
#Sta/Elev= 22
  4814.9   106.7  4824.9   102.3  4844.9    96.2  4859.9      94  4864.9    93.5
  4871.9   92.32    4887   92.23  4927.8   92.03  4955.8   84.03    4988   77.61
  4990.6    77.3  4993.2    75.3  5000.8   74.65    5006    75.5  5009.3    77.3
  5017.7   79.43  5039.1   83.08  5062.6   92.05  5113.1    96.8  5137.5  102.55
  5139.9   102.5  5144.9   102.7
#Mann= 4 , 1 , 0
  4814.9      .2       0  4814.9     .05       0  4927.8    .035       0
  5062.6     .05       0
Bank Sta=4927.8,5062.6
XS Rating Curve= 0
Exp/Cntr=.3,.1

Type RM Length L Ch R = 1 ,17291.8 ,967.2,964.9,963.5
BEGIN DESCRIPTION:
Cross Section 17291.8
END DESCRIPTION:
XS GIS Cut Line= 2
      3027840.23     13827246.97      3028041.04     13826997.82
#Sta/Elev= 23
  4814.9   105.4  4824.9   101.5  4829.9    99.7  4834.9    98.1  4839.9    96.9
  4859.9    94.1    4869    93.1  4893.4   92.06  4925.7   91.94  4957.5   80.48
  4984.5   77.18  4991.6    76.6  4994.7   75.38  4999.5   74.12  5006.3   73.94
  5008.4   76.54  5013.2   78.19  5039.6   83.39  5061.5   92.36  5110.7    97.8
    5125  100.77  5129.9   100.4  5134.9   100.7
#Mann= 3 , 1 , 0
  4814.9     .05       0  4925.7    .035       0  5061.5     .05       0
Bank Sta=4925.7,5061.5
XS Rating Curve= 0
Exp/Cntr=.3,.1