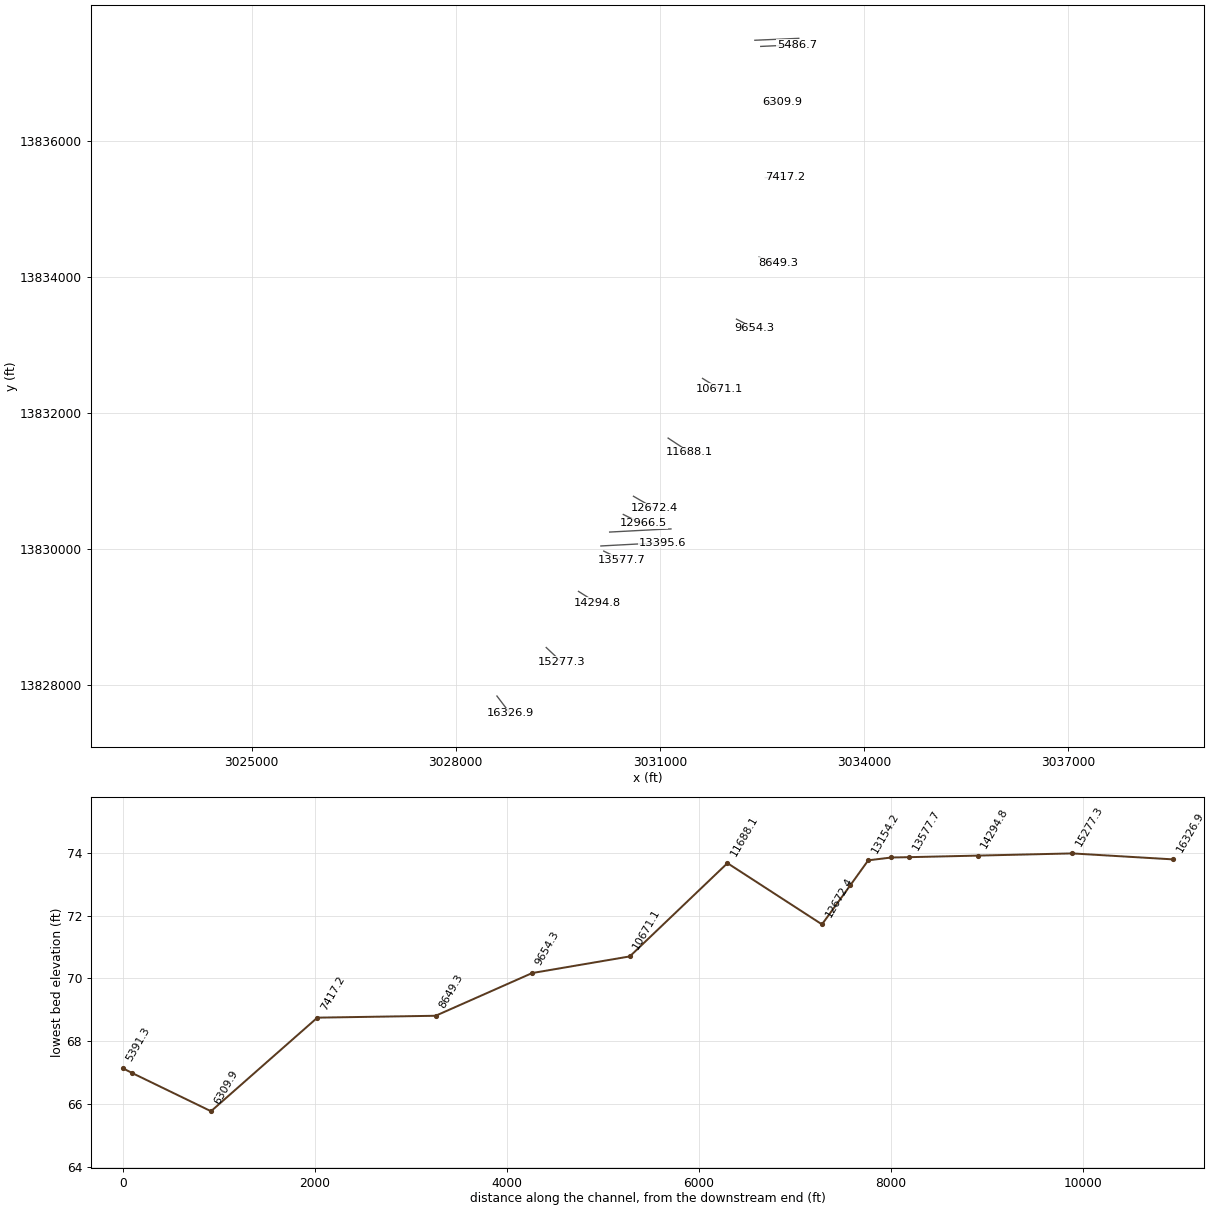
HEC-RAS study W190-00-00.PRJ: W190-00-00

--- W190-00-00.g01 (geometry) --- (continued)

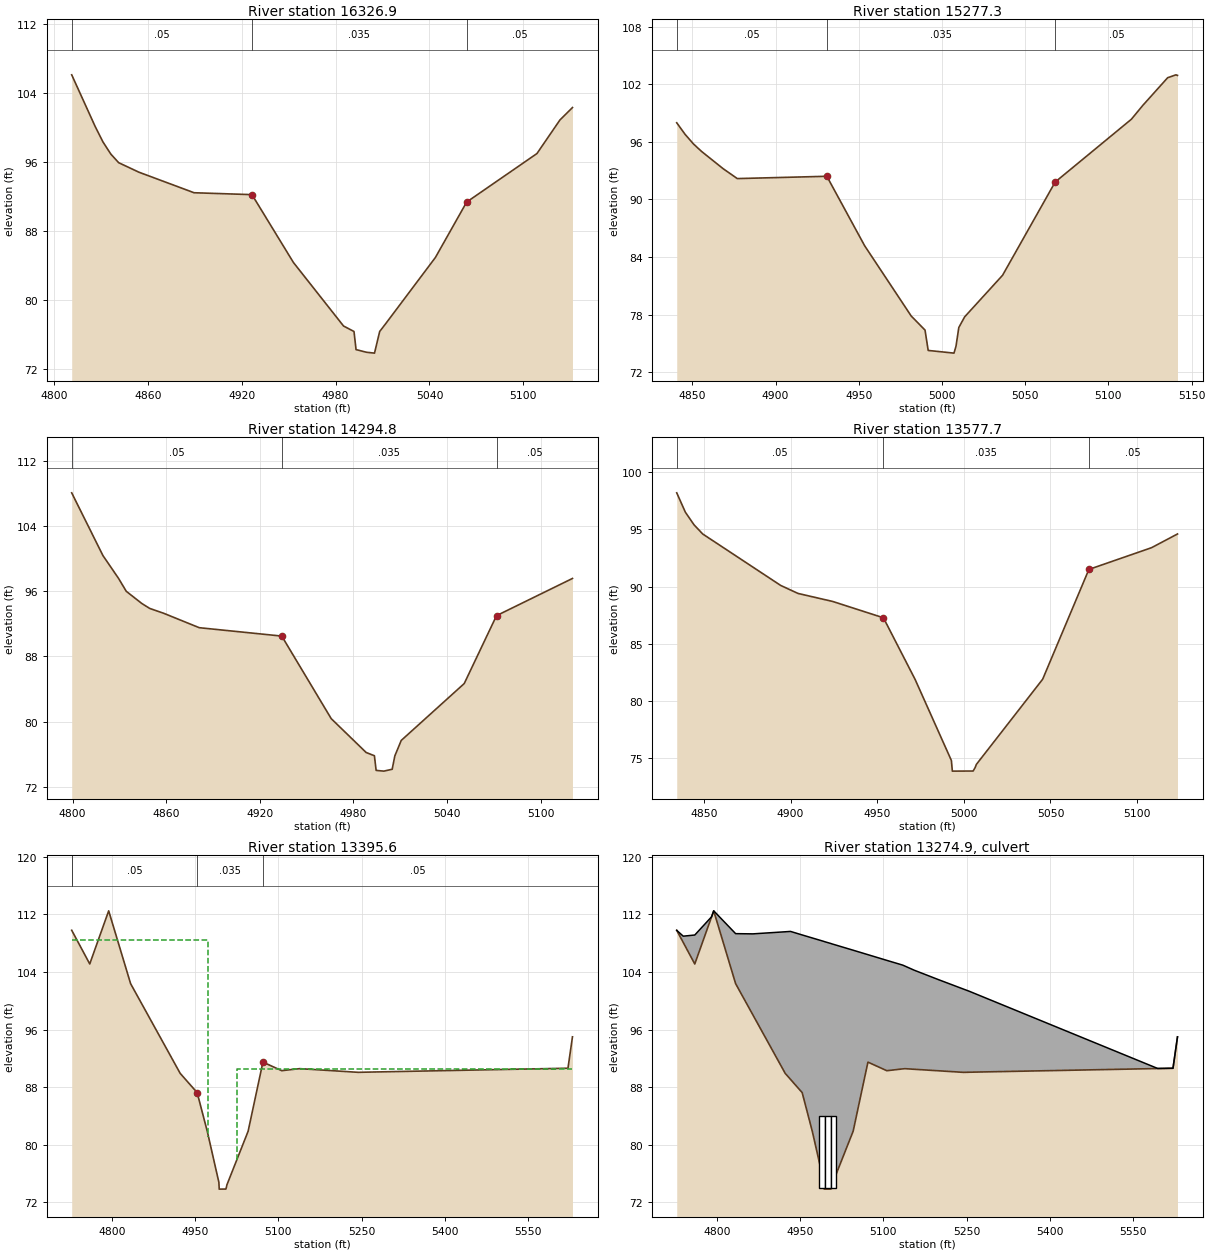
Type RM Length L Ch R = 1 ,16326.9 ,1035.2,1049.6,1061.6
BEGIN DESCRIPTION:
Cross Section 16326.9
END DESCRIPTION:
XS GIS Cut Line= 2
      3028605.31     13827843.46      3028799.02     13827588.76
#Sta/Elev= 21
  4811.4   106.1  4826.4   100.1  4831.4    98.3  4836.4    96.9  4841.4    95.9
  4854.3    94.8  4889.6   92.41  4926.6   92.19  4953.1   84.31  4985.1   76.94
  4991.8    76.3  4993.1    74.2  4999.8   73.89  5004.9   73.79  5008.2    76.3
  5011.8   77.15  5043.8   84.89  5063.8   91.33  5108.7   96.96  5123.4  100.86
  5131.4   102.3
#Mann= 3 , 1 , 0
  4811.4     .05       0  4926.6    .035       0  5063.8     .05       0
Bank Sta=4926.6,5063.8
XS Rating Curve= 0
Exp/Cntr=.3,.1

Type RM Length L Ch R = 1 ,15277.3 ,970.3,982.5,994.7
BEGIN DESCRIPTION:
Cross Section 15277.3
END DESCRIPTION:
XS GIS Cut Line= 2
      3029330.05      13828555.8      3029549.47     13828349.89
#Sta/Elev= 22
  4840.6      98  4845.6    96.8  4850.6    95.8  4855.6      95  4868.5   93.21
    4877   92.18  4930.8   92.42  4953.5   85.18  4981.5   77.85  4989.8   76.38
  4991.7   74.26  5007.2   73.98  5008.4   74.69  5010.1   76.65  5013.6   77.76
  5036.4    82.1    5068   91.82  5113.8   98.37  5120.6    99.8  5135.6   102.7
  5140.6     103  5141.5  102.94
#Mann= 3 , 1 , 0
  4840.6     .05       0  4930.8    .035       0    5068     .05       0
Bank Sta=4930.8,5068
XS Rating Curve= 0
Exp/Cntr=.3,.1

Type RM Length L Ch R = 1 ,14294.8 ,709.7,717.1,723.1
BEGIN DESCRIPTION:
Cross Section 14294.8
END DESCRIPTION:
XS GIS Cut Line= 2
      3029804.57     13829380.28      3030076.06     13829208.82
#Sta/Elev= 20
  4799.4   108.1  4819.4   100.4  4829.4    97.6  4834.4      96  4844.4    94.5
  4849.4    93.9  4858.4    93.3  4881.2   91.53  4934.1    90.5  4965.8   80.36
  4988.2    76.2  4993.5    75.8  4994.6      74  4999.5   73.91  5004.9   74.14
  5006.6   75.78  5010.7   77.68  5051.1   84.67  5071.8   93.01  5120.5   97.58
#Mann= 3 , 1 , 0
  4799.4     .05       0  4934.1    .035       0  5071.8     .05       0
Bank Sta=4934.1,5071.8
XS Rating Curve= 0
Exp/Cntr=.3,.1

Type RM Length L Ch R = 1 ,13577.7 ,85.7,182.1,163.4
BEGIN DESCRIPTION:
Cross Section 13577.7-Interpolated
END DESCRIPTION:
XS GIS Cut Line= 4
      3030175.98     13829971.83       3030281.8       13829920.
      3030376.81      13829872.5      3030434.98     13829843.62
#Sta/Elev= 18
  4834.3    98.2  4839.3    96.5  4844.3    95.4  4849.3    94.6  4894.3    90.1
  4904.3    89.4  4924.3    88.7 4953.59   87.27 4971.88   81.88 4992.81   74.79
 4993.36   73.86 5005.37   73.87 5006.55   74.18 5007.19   74.44  5045.5    81.9
 5072.16    91.5  5108.3    93.4  5123.3    94.6
#Mann= 3 , 1 , 0
  4834.3     .05       0 4953.59    .035       0 5072.16     .05       0
Bank Sta=4953.59,5072.16
XS Rating Curve= 0
Exp/Cntr=.5,.3

Type RM Length L Ch R = 1 ,13395.6 ,241.4,241.4,241.4
BEGIN DESCRIPTION:
Upstream Section of Bridge/Culvert/Weir
END DESCRIPTION:
XS GIS Cut Line= 3
      3030133.61     13830047.45      3030864.49     13830086.36
      3031035.07     13830093.36
#Sta/Elev= 28
  4727.5   109.8  4739.2  108.12 4760.03  105.12  4790.3  111.67 4794.16   112.5
 4833.65  102.39  4864.7   98.06 4923.01   89.93  4932.6   89.09 4953.59   87.26
 4971.88   81.87 4992.81   74.78 4993.36   73.85 5005.37   73.86 5006.55   74.17
 5007.19   74.43  5045.5   81.89 5072.16   91.49 5106.11    90.3  5134.8   90.55
 5138.68   90.58  5155.3    90.5    5199   90.29  5244.3   90.07  5254.7   90.09
  5594.4    90.6    5622   90.64  5630.1      95
#Mann= 4 , 1 , 0
  4727.5      .2       0  4727.5     .05       0 4953.59    .035       0
 5072.16     .05       0
#XS Ineff= 2 , 0
       0    4974   108.5    5025       0    90.6
Permanent Ineff=
       F       F
Bank Sta=4953.59,5072.16
XS Rating Curve= 0
Exp/Cntr=.5,.3

Type RM Length L Ch R = 2 ,13274.9 ,,,
BEGIN DESCRIPTION:
WESTHEIMER PARKWAY, SKEW ANGLE OF 25 DEGREES
Structure ID: W90-4
END DESCRIPTION:
Bridge Culvert--1,0,-1,-1, 0
Deck Dist Width WeirC Skew NumUp NumDn MinLoCord MaxHiCord MaxSubmerge Is_Ogee
10,221.4,3,0, 28, 28, , , .95, 0, 1,1,,
  4727.5  4739.2 4760.03  4790.3 4794.16 4833.65  4864.7 4923.01  4932.6 4953.59
 4971.88 4992.81 4993.36 5005.37 5006.55 5007.19  5045.5 5072.16 5106.11  5134.8
 5138.68  5155.3    5199  5244.3  5254.7  5594.4    5622  5630.1
   109.8  108.99  109.15  111.68  112.51  109.34  109.31   109.6  109.65  109.16
  108.74  108.26  108.24  107.97  107.94  107.92  107.04  106.42  105.63  104.97
  104.84  104.27  102.96  101.64  101.34   90.61   90.64      95
   109.8  108.12  105.12  111.67   112.5  102.39   98.06   89.93   89.09   87.26
   81.87   74.78   73.85   73.86   74.17   74.43   81.89   91.49    90.3   90.55
   90.58    90.5   90.29   90.07   90.09    90.6   90.64      95
  4727.5  4739.2 4760.03  4790.3 4794.16 4833.65  4864.7 4923.01  4932.6 4953.59
 4971.88 4992.81 4993.36 5005.37 5006.55 5007.19  5045.5 5072.16 5106.11  5134.8
 5138.68  5155.3    5199  5244.3  5254.7  5594.4    5622  5630.1
   109.8  108.99  109.15  111.68  112.51  109.34  109.31   109.6  109.65  109.16
  108.74  108.26  108.24  107.97  107.94  107.92  107.04  106.42  105.63  104.97
  104.84  104.27  102.96  101.64  101.34   90.61   90.64      95
  109.75  108.07  105.07  111.62  112.45  102.34   98.01   89.88   89.04   87.21
   81.82   74.73    73.8   73.81   74.12   74.38   81.84   91.44   90.25    90.5
   90.53   90.45   90.24   90.02   90.04   90.55   90.59   94.95
BR Coef= 1 , 0 , 0 ,1.25, 0 ,,,.8,-1,2,0,
WSPro=,,,, 1 ,,,, 0 ,,,, 0 ,,,,-1 ,-1 ,-1 , 0 , 0 , 0 , 0 , 0
Culvert=2,10,10,221.4,.015,.4,1,8,1,74.04,4989.4,74.05,4989.4,Culvert #1  , 0 ,10
Culvert Bottom n=.015
Culvert=2,10,10,221.4,.015,.4,1,8,1,74.04,5000,74.05,5000,Culvert #2  , 0 ,10
Culvert Bottom n=.015
Culvert=2,10,10,221.4,.015,.4,1,8,1,74.04,5010.4,74.05,5010.4,Culvert #3  , 0 ,10
Culvert Bottom n=.015
BR U #Sta/Elev= 28
  4727.5   109.8  4739.2  108.12 4760.03  105.12  4790.3  111.67 4794.16   112.5
 4833.65  102.39  4864.7   98.06 4923.01   89.93  4932.6   89.09 4953.59   87.26
 4971.88   81.87 4992.81   74.78 4993.36   73.85 5005.37   73.86 5006.55   74.17
 5007.19   74.43  5045.5   81.89 5072.16   91.49 5106.11    90.3  5134.8   90.55
 5138.68   90.58  5155.3    90.5    5199   90.29  5244.3   90.07  5254.7   90.09
  5594.4    90.6    5622   90.64  5630.1      95
BR U #Mann= 4
  4727.5      .2  4727.5     .05 4953.59    .035 5072.16     .05
BR U Banks=4953.59,5072.16
BR D #Sta/Elev= 28
  4727.5  109.75  4739.2  108.07 4760.03  105.07  4790.3  111.62 4794.16  112.45
 4833.65  102.34  4864.7   98.01 4923.01   89.88  4932.6   89.04 4953.59   87.21
 4971.88   81.82 4992.81   74.73 4993.36    73.8 5005.37   73.81 5006.55   74.12
 5007.19   74.38  5045.5   81.84 5072.16   91.44 5106.11   90.25  5134.8    90.5
 5138.68   90.53  5155.3   90.45    5199   90.24  5244.3   90.02  5254.7   90.04
  5594.4   90.55    5622   90.59  5630.1   94.95
BR D #Mann= 4
  4727.5      .2  4727.5     .05 4953.59    .035 5072.16     .05
BR D Banks=4953.59,5072.16
BC Design=,, 0 ,, 0 ,,,,,,
BC HTab HWMax=112.5

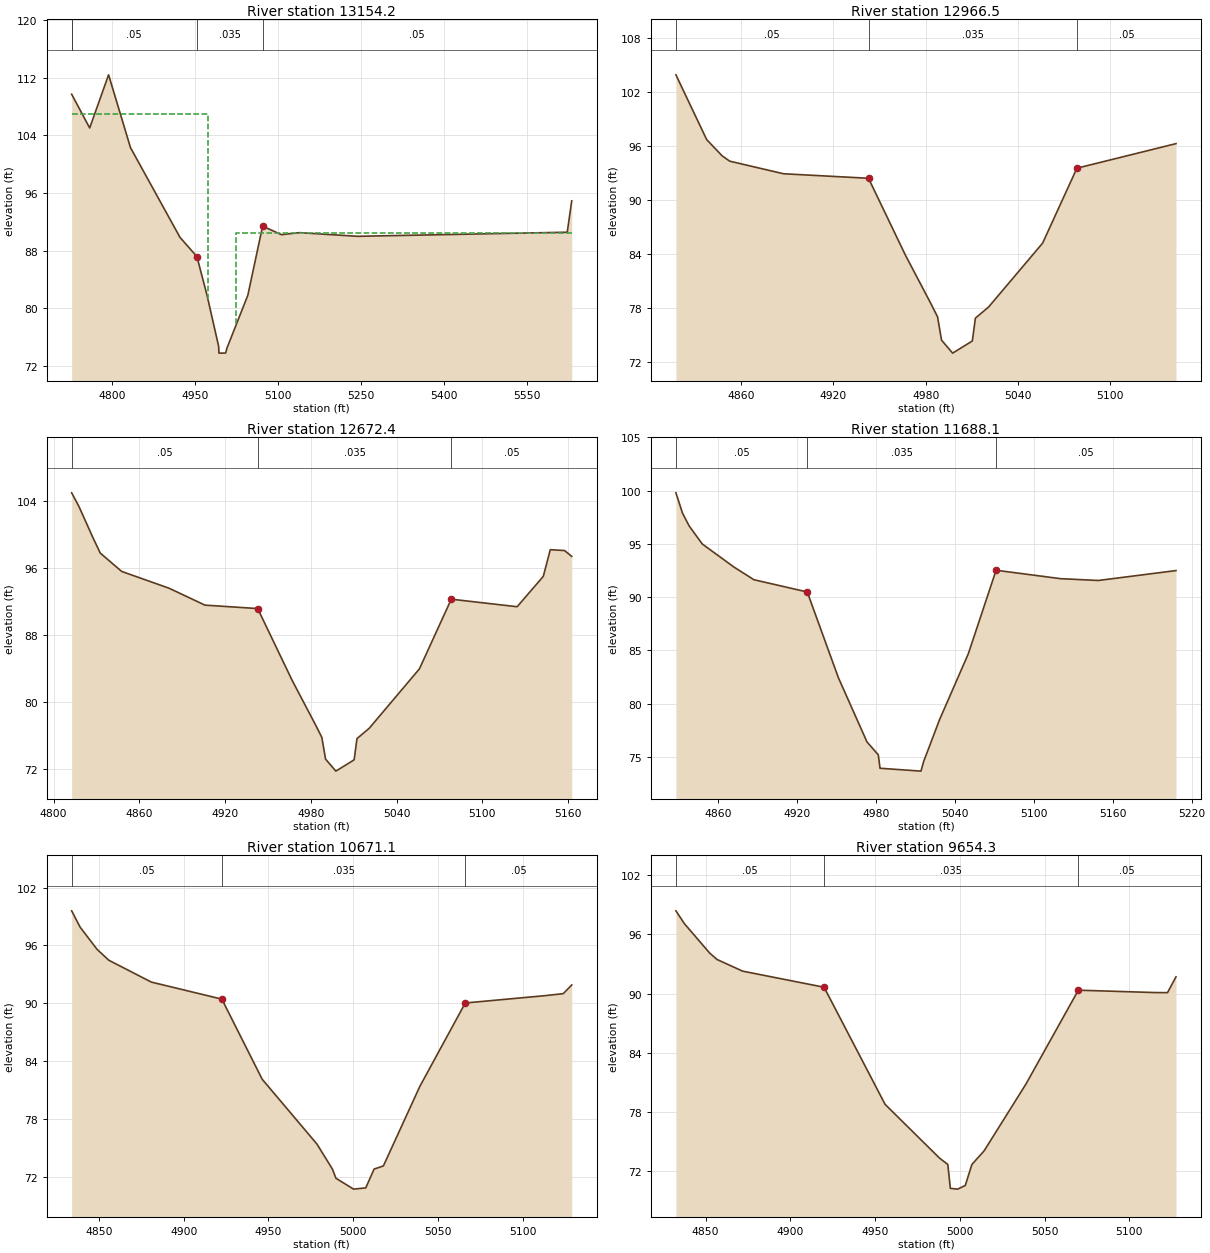
Type RM Length L Ch R = 1 ,13154.2 ,187.7,187.7,187.7
BEGIN DESCRIPTION:
Downstream Section of Bridge/Culvert/Weir
END DESCRIPTION:
XS GIS Cut Line= 3
      3030262.51     13830251.55      3030993.39     13830290.46
      3031163.98     13830297.47
#Sta/Elev= 28
  4727.5  109.71  4739.2  108.03 4760.03  105.03  4790.3  111.58 4794.16  112.41
 4833.65   102.3  4864.7   97.97 4923.01   89.84  4932.6      89 4953.59   87.17
 4971.88   81.78 4992.81   74.69 4993.36   73.76 5005.37   73.77 5006.55   74.08
 5007.19   74.34  5045.5    81.8 5072.16    91.4 5106.11   90.21  5134.8   90.46
 5138.68   90.49  5155.3   90.41    5199    90.2  5244.3   89.98  5254.7      90
  5594.4   90.51    5622   90.55  5630.1   94.91
#Mann= 4 , 1 , 0
  4727.5      .2       0  4727.5     .05       0 4953.59    .035       0
 5072.16     .05       0
#XS Ineff= 2 , 0
       0    4974     107    5025       0    90.4
Permanent Ineff=
       F       F
Bank Sta=4953.59,5072.16
XS Rating Curve= 0
Exp/Cntr=.5,.3

Type RM Length L Ch R = 1 ,12966.5 ,299.3,294.1,288.8
BEGIN DESCRIPTION:
Cross Section 12966.5-Interpolated
END DESCRIPTION:
XS GIS Cut Line= 4
      3030463.29     13830510.14      3030585.82     13830448.87
      3030687.16     13830401.36      3030760.33     13830380.15
#Sta/Elev= 17
  4817.6   103.9  4837.6    96.7  4847.6    94.9  4852.6    94.3  4887.6    92.9
  4942.8    92.4  4966.9   83.82  4983.6   78.39  4987.7   76.99  4990.3    74.4
  4997.5   72.96  5010.3   74.31  5012.3   76.85  5020.9   78.09    5056   85.19
  5078.3   93.52  5142.7   96.25
#Mann= 3 , 1 , 0
  4817.6     .05       0  4942.8    .035       0  5078.3     .05       0
Bank Sta=4942.8,5078.3
XS Rating Curve= 0
Exp/Cntr=.3,.1

Type RM Length L Ch R = 1 ,12672.4 ,988.6,984.3,981.4
BEGIN DESCRIPTION:
Cross Section 12672.4
END DESCRIPTION:
XS GIS Cut Line= 2
      3030612.88     13830777.29      3030916.05     13830602.39
#Sta/Elev= 23
  4812.6     105  4817.6   103.4  4827.6    99.6  4832.6    97.8  4847.6    95.6
  4880.8   93.59  4905.9   91.57  4942.8   91.16  4966.9   82.58  4983.6   77.15
  4987.7   75.75  4990.3   73.16  4997.5   71.72  5010.3   73.07  5012.3   75.61
  5020.9   76.85    5056   83.95  5078.3   92.28  5124.4   91.38  5142.7   95.01
  5147.6    98.2  5157.6    98.1  5162.6    97.4
#Mann= 3 , 1 , 0
  4812.6     .05       0  4942.8    .035       0  5078.3     .05       0
Bank Sta=4942.8,5078.3
XS Rating Curve= 0
Exp/Cntr=.3,.1

Type RM Length L Ch R = 1 ,11688.1 ,1015.8,1017,1018.3
BEGIN DESCRIPTION:
Cross Section 11688.1
END DESCRIPTION:
XS GIS Cut Line= 2
      3031122.24     13831631.58      3031439.52     13831422.46
#Sta/Elev= 20
    4828    99.8    4833    97.9    4838    96.7    4848      95  4872.1   92.83
  4887.3   91.64  4927.8   90.49  4951.5   82.43  4973.2   76.41  4981.8    75.2
  4983.1   73.94  5014.2   73.67  5016.5   74.67  5018.2    75.2  5028.3   78.49
  5050.2   84.69  5071.3   92.53  5120.3   91.74    5149   91.57    5208    92.5
#Mann= 3 , 1 , 0
    4828     .05       0  4927.8    .035       0  5071.3     .05       0
Bank Sta=4927.8,5071.3
XS Rating Curve= 0
Exp/Cntr=.3,.1

Type RM Length L Ch R = 1 ,10671.1 ,1011.3,1016.8,1021.2
BEGIN DESCRIPTION:
Cross Section 10671.1
END DESCRIPTION:
XS GIS Cut Line= 2
      3031628.44     13832508.18      3031878.98     13832352.44
#Sta/Elev= 19
  4833.9    99.6  4838.9    97.9  4848.9    95.6  4855.8   94.47  4880.9    92.2
  4922.5   90.43  4946.3   82.11  4978.6   75.38  4987.7   72.79  4989.8   71.83
  5000.2    70.7  5007.4   70.83  5012.3   72.78  5017.8   73.11  5039.3   81.37
  5066.1   90.03  5113.1   90.79  5123.9      91  5128.9    91.9
#Mann= 3 , 1 , 0
  4833.9     .05       0  4922.5    .035       0  5066.1     .05       0
Bank Sta=4922.5,5066.1
XS Rating Curve= 0
Exp/Cntr=.3,.1

Type RM Length L Ch R = 1 ,9654.3  ,987,1005,1019.4
BEGIN DESCRIPTION:
Cross Section 9654.3
END DESCRIPTION:
XS GIS Cut Line= 2
      3032127.51     13833378.85      3032389.53     13833243.33
#Sta/Elev= 19
  4832.5    98.4  4837.5    97.1  4852.5    94.1  4856.8   93.46  4871.9   92.28
  4919.9   90.65  4955.9   78.77    4988   73.32  4992.9   72.67  4994.4   70.25
  4998.7   70.17  5003.2   70.54  5007.1   72.67  5014.3   74.05    5039   80.83
  5069.9   90.35  5114.9   90.11  5122.5    90.1  5127.5    91.7
#Mann= 3 , 1 , 0
  4832.5     .05       0  4919.9    .035       0  5069.9     .05       0
Bank Sta=4919.9,5069.9
XS Rating Curve= 0
Exp/Cntr=.3,.1

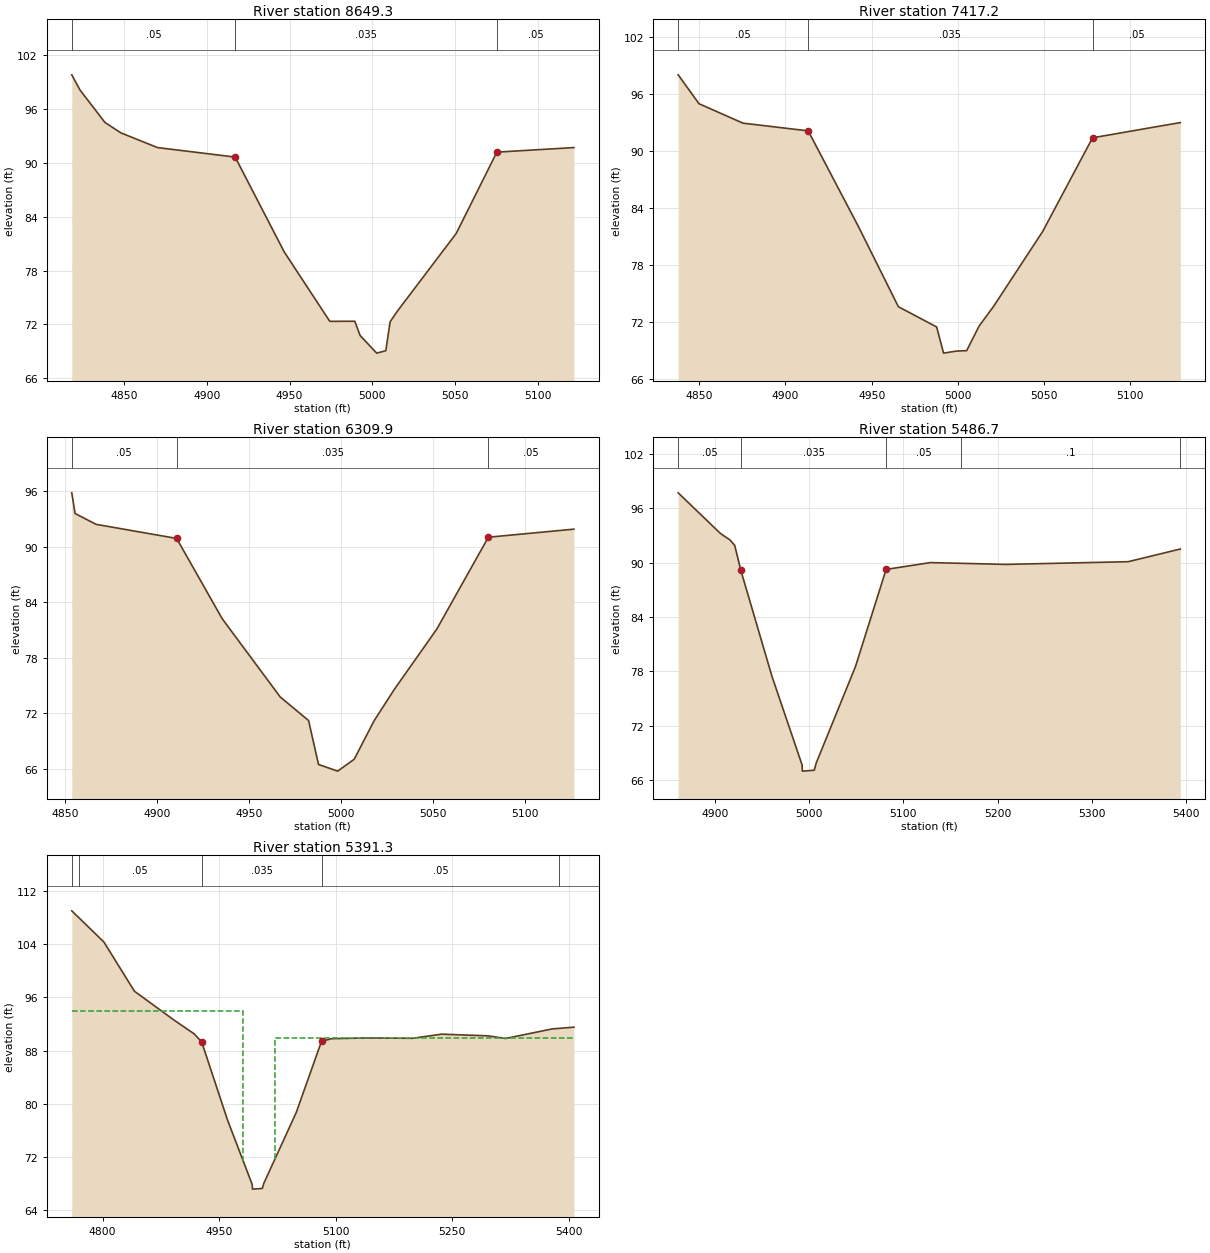
Type RM Length L Ch R = 1 ,8649.3  ,1204.1,1232.1,1252
BEGIN DESCRIPTION:
Cross Section 8649.3
END DESCRIPTION:
XS GIS Cut Line= 2
      3032456.82     13834289.08      3032748.05     13834205.48
#Sta/Elev= 17
  4818.6    99.8  4823.6    98.1  4838.6    94.5  4848.2   93.34  4870.3    91.7
  4917.2   90.64  4946.8   80.08  4974.3   72.35  4989.4   72.36  4992.6   70.77
  5002.6   68.81  5008.1   69.08  5010.7    72.3  5015.1   73.49  5050.6   82.14
  5075.1   91.19  5121.6    91.7
#Mann= 3 , 1 , 0
  4818.6     .05       0  4917.2    .035       0  5075.1     .05       0
Bank Sta=4917.2,5075.1
XS Rating Curve= 0
Exp/Cntr=.3,.1

Type RM Length L Ch R = 1 ,7417.2  ,1110.2,1107.3,1104.1
BEGIN DESCRIPTION:
Cross Section 7417.2
END DESCRIPTION:
XS GIS Cut Line= 2
      3032550.15     13835456.57      3032841.08     13835469.04
#Sta/Elev= 16
  4837.8      98  4849.9   94.96  4875.4   92.92  4913.2   92.11  4942.4   82.03
  4965.5   73.63  4987.7    71.5  4991.7   68.75    4999   68.96  5005.1   69.01
  5012.3   71.59  5020.7   73.66  5049.2   81.54  5078.1   91.38  5119.7   92.69
    5129   92.98
#Mann= 3 , 1 , 0
  4837.8     .05       0  4913.2    .035       0  5078.1     .05       0
Bank Sta=4913.2,5078.1
XS Rating Curve= 0
Exp/Cntr=.3,.1

Type RM Length L Ch R = 1 ,6309.9  ,818.5,823.2,825.1
BEGIN DESCRIPTION:
Cross Section 6309.9
END DESCRIPTION:
XS GIS Cut Line= 2
      3032523.78     13836569.54      3032796.68     13836569.54
#Sta/Elev= 15
  4853.5    95.8  4855.3   93.57  4866.7    92.4  4910.5   90.88  4935.3    82.2
  4966.8   73.77  4982.2   71.23  4987.6   66.49    4998   65.77    5007   67.05
  5017.8    71.2  5028.8   74.59  5051.9    81.1  5079.9   91.01  5126.4   91.88
#Mann= 3 , 1 , 0
  4853.5     .05       0  4910.5    .035       0  5079.9     .05       0
Bank Sta=4910.5,5079.9
XS Rating Curve= 0
Exp/Cntr=.3,.1

Type RM Length L Ch R = 1 ,5486.7  ,56.8,95.4,60.3
BEGIN DESCRIPTION:
Cross Section 5486.7-Interpolated
END DESCRIPTION:
XS GIS Cut Line= 4
      3032484.11     13837383.83      3032580.43     13837388.35
      3032686.25     13837393.39      3033016.31     13837405.98
#Sta/Elev= 18
  4861.1    97.7  4906.1    93.2  4916.1    92.5  4921.1    91.9  4927.5   89.17
  4960.6   77.45  4992.5   67.69  4992.9   66.99  4994.4      67  5005.5   67.09
  5007.5   67.87  5049.2   78.53  5081.7   89.25  5128.5      90  5161.6   89.92
  5208.5    89.8  5338.5    90.1  5393.8    91.5
#Mann= 5 , 1 , 0
  4861.1     .05       0  4927.5    .035       0  5081.7     .05       0
  5161.6      .1       0  5393.8      .2       0
Bank Sta=4927.5,5081.7
XS Rating Curve= 0
Exp/Cntr=.5,.3

Type RM Length L Ch R = 1 ,5391.3  ,112,112,112
BEGIN DESCRIPTION:
Upstream Section of Bridge/Culvert/Weir
END DESCRIPTION:
XS GIS Cut Line= 2
       3032397.5      13837474.4      3033042.88     13837502.59
#Sta/Elev= 23
  4760.4  109.04  4769.6     108  4801.7  104.35    4841   96.94  4892.1   92.58
  4917.6   90.54  4927.5   89.32  4960.6    77.6  4992.5   67.84  4992.9   67.14
  5005.5   67.24  5007.5   68.02  5049.2   78.68  5081.7    89.4  5094.9   89.79
  5139.6    89.9  5199.1   89.85  5236.1   90.47  5295.6   90.22  5318.5   89.82
  5378.5   91.26  5387.7   91.35  5406.4   91.52
#Mann= 5 , 1 , 0
  4760.4      .2       0  4769.6     .05       0  4927.5    .035       0
  5081.7     .05       0  5387.7      .2       0
#XS Ineff= 2 , 0
       0    4981      94    5022       0    89.9
Permanent Ineff=
       F       F
Bank Sta=4927.5,5081.7
XS Rating Curve= 0
Exp/Cntr=.5,.3