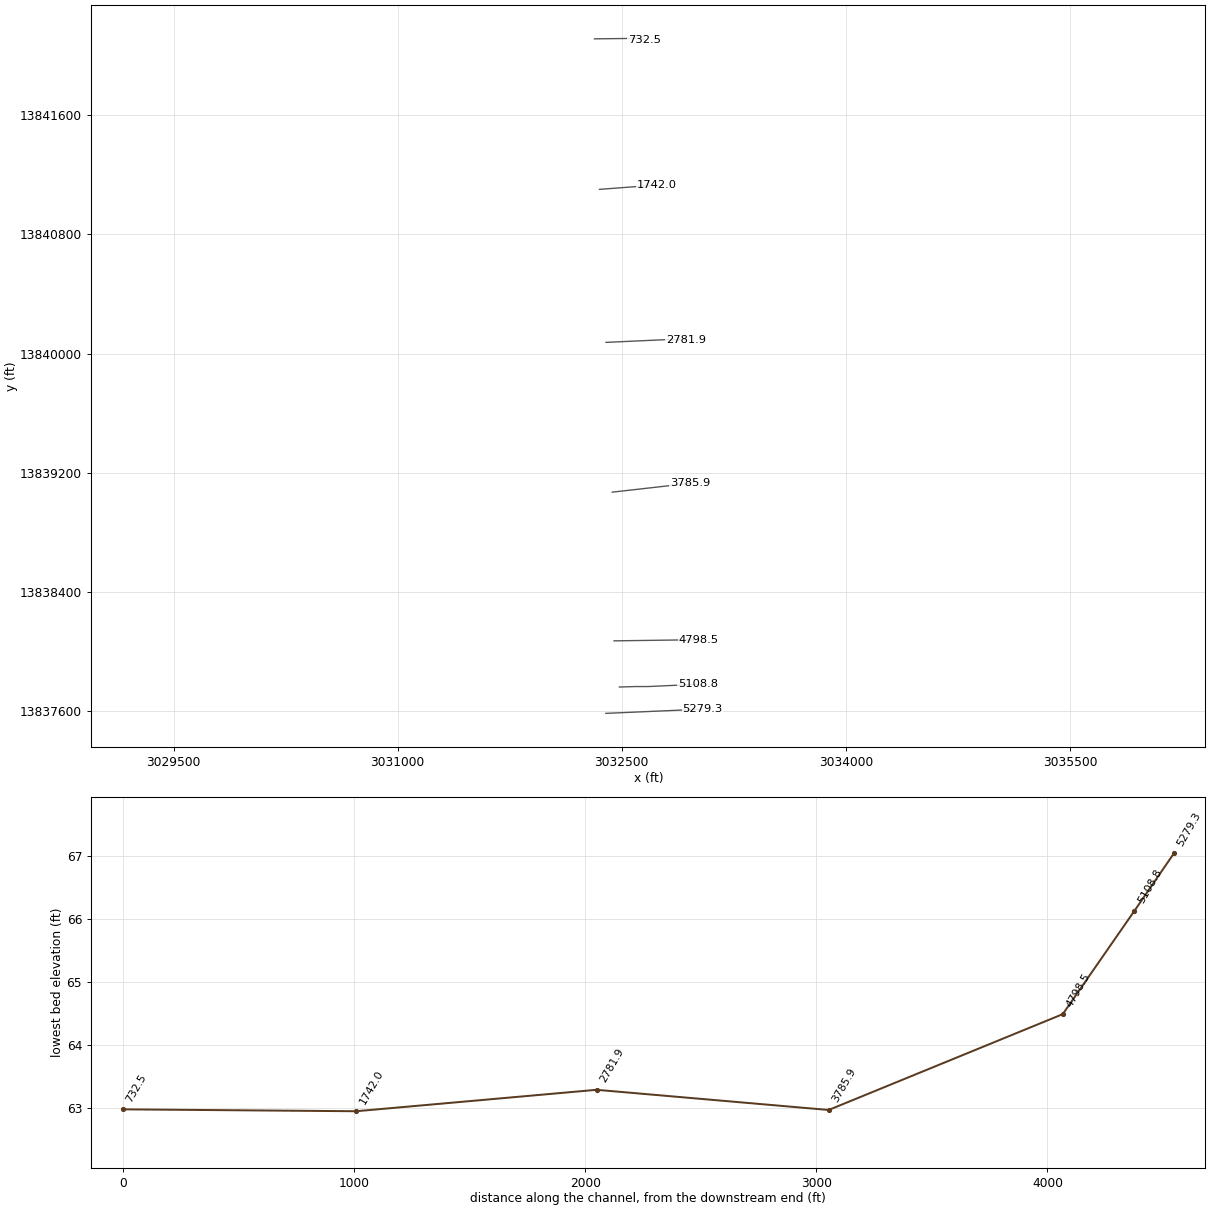
HEC-RAS study W190-00-00.PRJ: W190-00-00

--- W190-00-00.g01 (geometry) --- (continued)

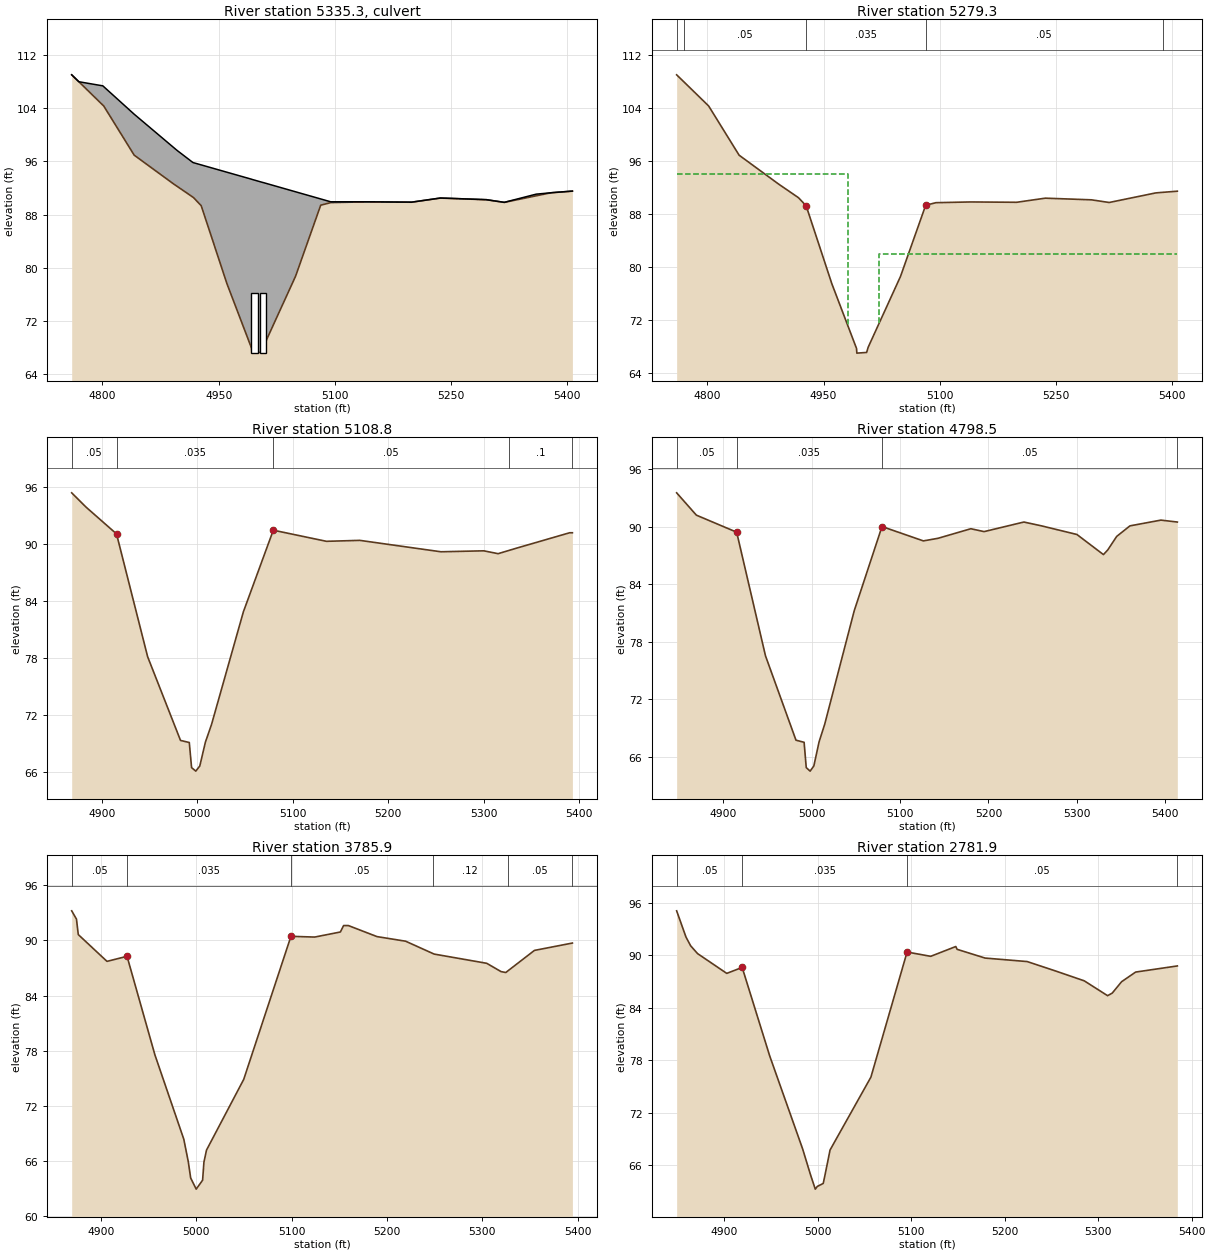
Type RM Length L Ch R = 2 ,5335.3  ,,,
BEGIN DESCRIPTION:
NOBLE-GOAR ROAD
Structure ID: W90-2
END DESCRIPTION:
Bridge Culvert--1,0,-1,-1, 0
Deck Dist Width WeirC Skew NumUp NumDn MinLoCord MaxHiCord MaxSubmerge Is_Ogee
10,92,3,0, 35, 35, , , .95, 0, 1,1,,
  4760.4  4769.6  4800.6  4801.7    4841  4841.1  4892.1  4896.5  4916.9  4917.6
  4927.5  4960.6  4992.5  4992.9  4994.4  5005.5  5007.5  5049.2  5081.7  5094.6
  5094.9  5139.6  5142.2  5184.5  5199.1  5236.1    5251  5295.6  5304.6  5318.5
  5359.6  5378.5  5387.7  5390.5  5406.4
  109.05  108.01  107.39  107.27  103.12  103.11   98.08   97.65   95.83   95.81
   95.48   94.38   93.32    93.3   93.25   92.88   92.82   91.43   90.35   89.92
   89.92   89.92   89.92   89.88   89.87   90.49   90.43   90.24   90.08   89.84
   91.07   91.28   91.37   91.39   91.53
  109.05  108.01  104.48  104.36   96.95   96.94   92.59   92.24   90.61   90.55
   89.33   77.61   67.85   67.15   67.16   67.25   68.03   78.69   89.41   89.79
    89.8   89.91   89.91   89.87   89.86   90.48   90.42   90.23   90.07   89.83
   90.82   91.27   91.36   91.38   91.53
  4760.4  4769.6  4800.6  4801.7    4841  4841.1  4892.1  4896.5  4916.9  4917.6
  4927.5  4960.6  4992.5  4992.9  4994.4  5005.5  5007.5  5049.2  5081.7  5094.6
  5094.9  5139.6  5142.2  5184.5  5199.1  5236.1    5251  5295.6  5304.6  5318.5
  5359.6  5378.5  5387.7  5390.5  5406.4
  109.05  108.01  107.39  107.27  103.12  103.11   98.08   97.65   95.83   95.81
   95.48   94.38   93.32    93.3   93.25   92.88   92.82   91.43   90.35   89.92
   89.92   89.92   89.92   89.88   89.87   90.49   90.43   90.24   90.08   89.84
   91.07   91.28   91.37   91.39   91.53
  108.99  107.95  104.42   104.3   96.89   96.88   92.53   92.18   90.55   90.49
   89.27   77.55   67.79   67.09    67.1   67.19   67.97   78.63   89.35   89.73
   89.74   89.85   89.85   89.81    89.8   90.42   90.36   90.17   90.01   89.77
   90.76   91.21    91.3   91.32   91.47
BR Coef= 1 , 0 , 0 ,1.25, 0 ,,,.8,-1,2,0,
WSPro=,,,, 1 ,,,, 0 ,,,, 0 ,,,,-1 ,-1 ,-1 , 0 , 0 , 0 , 0 , 0
Culvert=2,9,9,92,.015,.4,1,8,1,67.12,4995.7,66.79,4995.7,Culvert #1  , 0 ,10
Culvert Bottom n=.015
Culvert=2,9,9,92,.015,.4,1,8,1,67.12,5007.2,66.79,5007.2,Culvert #2  , 0 ,10
Culvert Bottom n=.015
BR U #Sta/Elev= 35
  4760.4  109.05  4769.6  108.01  4800.6  104.48  4801.7  104.36    4841   96.95
  4841.1   96.94  4892.1   92.59  4896.5   92.24  4916.9   90.61  4917.6   90.55
  4927.5   89.33  4960.6   77.61  4992.5   67.85  4992.9   67.15  4994.4   67.16
  5005.5   67.25  5007.5   68.03  5049.2   78.69  5081.7   89.41  5094.6   89.79
  5094.9    89.8  5139.6   89.91  5142.2   89.91  5184.5   89.87  5199.1   89.86
  5236.1   90.48    5251   90.42  5295.6   90.23  5304.6   90.07  5318.5   89.83
  5359.6   90.82  5378.5   91.27  5387.7   91.36  5390.5   91.38  5406.4   91.53
BR U #Mann= 5
  4760.4      .2  4769.6     .05  4927.5    .035  5081.7     .05  5387.7      .2
BR U Banks=4927.5,5081.7
BR D #Sta/Elev= 35
  4760.4  108.99  4769.6  107.95  4800.6  104.42  4801.7   104.3    4841   96.89
  4841.1   96.88  4892.1   92.53  4896.5   92.18  4916.9   90.55  4917.6   90.49
  4927.5   89.27  4960.6   77.55  4992.5   67.79  4992.9   67.09  4994.4    67.1
  5005.5   67.19  5007.5   67.97  5049.2   78.63  5081.7   89.35  5094.6   89.73
  5094.9   89.74  5139.6   89.85  5142.2   89.85  5184.5   89.81  5199.1    89.8
  5236.1   90.42    5251   90.36  5295.6   90.17  5304.6   90.01  5318.5   89.77
  5359.6   90.76  5378.5   91.21  5387.7    91.3  5390.5   91.32  5406.4   91.47
BR D #Mann= 5
  4760.4      .2  4769.6     .05  4927.5    .035  5081.7     .05  5387.7      .2
BR D Banks=4927.5,5081.7
BC Design=,, 0 ,, 0 ,,,,,,
BC HTab HWMax=109.04

Type RM Length L Ch R = 1 ,5279.3  ,170.5,170.5,170.5
BEGIN DESCRIPTION:
Downstream Section of Bridge/Culvert/Weir
END DESCRIPTION:
XS GIS Cut Line= 2
      3032393.42     13837586.32       3033038.8     13837614.52
#Sta/Elev= 23
  4760.4  108.94  4769.6   107.9  4801.7  104.25    4841   96.84  4892.1   92.48
  4917.6   90.44  4927.5   89.22  4960.6    77.5  4992.5   67.74  4992.9   67.04
  5005.5   67.14  5007.5   67.92  5049.2   78.58  5081.7    89.3  5094.9   89.69
  5139.6    89.8  5199.1   89.75  5236.1   90.37  5295.6   90.12  5318.5   89.72
  5378.5   91.16  5387.7   91.25  5406.4   91.42
#Mann= 5 , 1 , 0
  4760.4      .2       0  4769.6     .05       0  4927.5    .035       0
  5081.7     .05       0  5387.7      .2       0
#XS Ineff= 2 , 0
       0    4981      94    5022       0      82
Permanent Ineff=
       F       F
Bank Sta=4927.5,5081.7
XS Rating Curve= 0
Exp/Cntr=.5,.3

Type RM Length L Ch R = 1 ,5108.8  ,309.4,310.3,309.7
BEGIN DESCRIPTION:
Cross Section 5108.8-Interpolated
END DESCRIPTION:
XS GIS Cut Line= 4
      3032484.16     13837763.15       3032590.5     13837766.28
      3032676.17     13837766.28      3033008.75      13837781.4
#Sta/Elev= 22
  4868.2    95.4  4883.2    93.9  4915.2   91.08  4947.8   78.17  4982.3   69.36
  4991.5   69.14  4993.9    66.5  4998.3   66.13  5002.5   66.67  5008.4   69.18
  5014.8   71.03  5048.2   82.88  5079.6   91.47  5135.3    90.3  5170.3    90.4
  5255.3    89.2  5300.3    89.3  5315.3      89  5326.3   89.33  5335.3    89.6
  5390.3    91.2  5393.2    91.2
#Mann= 5 , 1 , 0
  4868.2     .05       0  4915.2    .035       0  5079.6     .05       0
  5326.3      .1       0  5393.2      .2       0
Bank Sta=4915.2,5079.6
XS Rating Curve= 0
Exp/Cntr=.3,.1

Type RM Length L Ch R = 1 ,4798.5  ,1004,1012.6,1019.1
BEGIN DESCRIPTION:
Cross Section 4798.5
END DESCRIPTION:
XS GIS Cut Line= 2
      3032448.34     13838072.84      3033014.62     13838080.44
#Sta/Elev= 26
  4847.3   93.55  4869.6   91.22  4915.2   89.44  4947.8   76.53  4982.3   67.72
  4991.5    67.5  4993.9   64.86  4998.3   64.49  5002.5   65.03  5008.4   67.54
  5014.8   69.39  5048.2   81.24  5079.6   90.03  5126.4   88.53  5142.9    88.8
  5180.1    89.8  5195.1    89.5  5240.1    90.5  5260.1    90.1  5300.1    89.2
  5330.1    87.1  5335.1    87.6  5345.1      89  5360.1    90.1  5395.1    90.7
  5413.7    90.5
#Mann= 4 , 1 , 0
  4847.3     .05       0  4915.2    .035       0  5079.6     .05       0
  5413.7      .2       0
Bank Sta=4915.2,5079.6
XS Rating Curve= 0
Exp/Cntr=.3,.1

Type RM Length L Ch R = 1 ,3785.9  ,1002.1,1004,991.8
BEGIN DESCRIPTION:
Cross Section 3785.9
END DESCRIPTION:
XS GIS Cut Line= 2
      3032436.46      13839070.3      3032957.92     13839129.48
#Sta/Elev= 29
  4869.6    93.2  4874.6    92.3  4876.5   90.62  4906.6   87.71  4927.6   88.26
  4956.8   77.56  4987.1   68.39  4991.8   65.95  4994.3   64.18  5000.1   62.97
  5006.8   63.94  5008.2    65.9  5010.9   67.21  5049.9   74.89  5099.4   90.43
  5124.3   90.35  5151.2    90.9  5154.6    91.6  5159.6    91.6  5189.6    90.4
  5219.6    89.9  5247.8   88.58  5249.6    88.5  5304.6    87.5  5319.6    86.6
  5324.6    86.5  5326.7   86.67  5354.6    88.9  5394.4    89.7
#Mann= 6 , 1 , 0
  4869.6     .05       0  4927.6    .035       0  5099.4     .05       0
  5247.8     .12       0  5326.7     .05       0  5394.4      .2       0
Bank Sta=4927.6,5099.4
XS Rating Curve= 0
Exp/Cntr=.3,.1

Type RM Length L Ch R = 1 ,2781.9  ,1029.7,1039.9,1034.6
BEGIN DESCRIPTION:
Cross Section 2781.9
END DESCRIPTION:
XS GIS Cut Line= 3
      3032394.41     13840075.03      3032799.96     13840093.46
      3032929.57     13840093.46
#Sta/Elev= 28
  4849.1    95.1  4859.1    92.1  4864.1    91.1  4871.5   90.21  4902.7   87.95
  4919.2   88.63  4948.6   78.53  4983.9   67.88  4992.1      65  4997.4   63.29
  4999.6    63.6  5005.9   63.94    5008      65  5013.2   67.76  5056.9   76.09
  5095.6   90.39  5120.9    89.9  5147.7   91.02  5149.1    90.7  5179.1    89.7
  5224.1    89.3  5255.1    88.2  5285.1    87.1  5310.1    85.4  5315.1    85.7
  5325.1      87  5340.1    88.1  5384.7    88.8
#Mann= 4 , 1 , 0
  4849.1     .05       0  4919.2    .035       0  5095.6     .05       0
  5384.7      .2       0
Bank Sta=4919.2,5095.6
XS Rating Curve= 0
Exp/Cntr=.3,.1

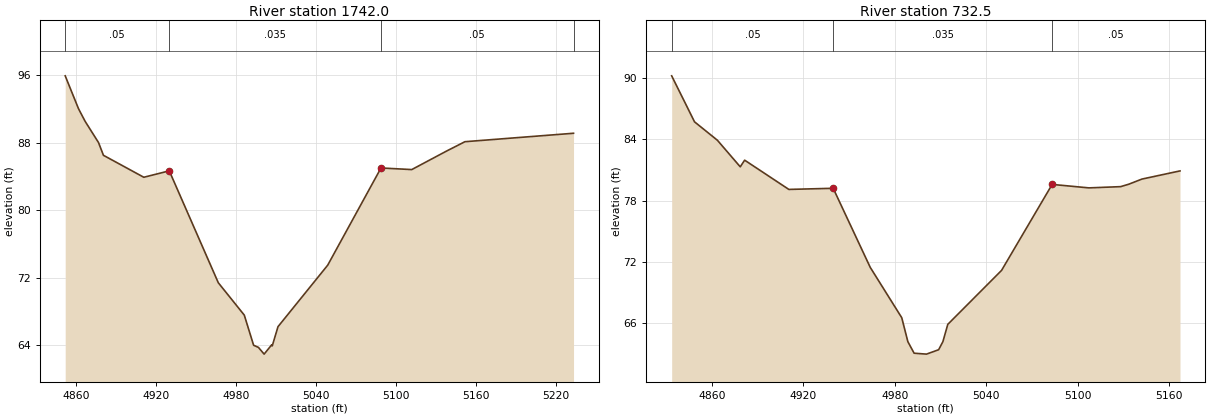
Type RM Length L Ch R = 1 ,1742.0  ,1006.7,1009.5,998.1
BEGIN DESCRIPTION:
Cross Section 1742.0
END DESCRIPTION:
XS GIS Cut Line= 2
      3032350.69     13841101.36       3032731.1     13841130.35
#Sta/Elev= 21
  4851.6    95.9  4861.6      92  4866.6    90.5  4876.6      88  4880.3   86.49
  4910.6   83.89  4929.7   84.65  4966.5    71.4    4986   67.57    4993      64
  4996.6   63.75  5000.9   62.95  5006.5   64.04    5007   63.93  5011.3    66.2
  5048.6   73.48  5088.6   84.99  5111.7    84.8  5137.3   86.95  5151.6    88.1
  5233.1    89.1
#Mann= 4 , 1 , 0
  4851.6     .05       0  4929.7    .035       0  5088.6     .05       0
  5233.1      .2       0
Bank Sta=4929.7,5088.6
XS Rating Curve= 0
Exp/Cntr=.3,.1

Type RM Length L Ch R = 1 ,732.5   ,0,0,0
BEGIN DESCRIPTION:
Cross Section 732.5
END DESCRIPTION:
XS GIS Cut Line= 3
      3032317.24     13842111.19      3032625.79     13842114.58
      3032649.47     13842106.47
#Sta/Elev= 22
  4833.5    90.2  4848.5    85.7  4863.5    83.9  4878.5    81.3  4881.4   81.95
  4910.4   79.09  4939.5    79.2  4963.8   71.47  4984.5   66.54  4988.5    64.2
  4992.6   63.07  5000.7   62.98  5008.7   63.41  5011.5    64.2  5014.7   65.89
    5050   71.17  5083.2   79.58  5107.3   79.24  5128.1   79.36  5133.5    79.6
  5142.1    80.1  5167.1    80.9
#Mann= 3 , 1 , 0
  4833.5     .05       0  4939.5    .035       0  5083.2     .05       0
Bank Sta=4939.5,5083.2
XS Rating Curve= 0
Exp/Cntr=.3,.1

Chan Stop Cuts=-1